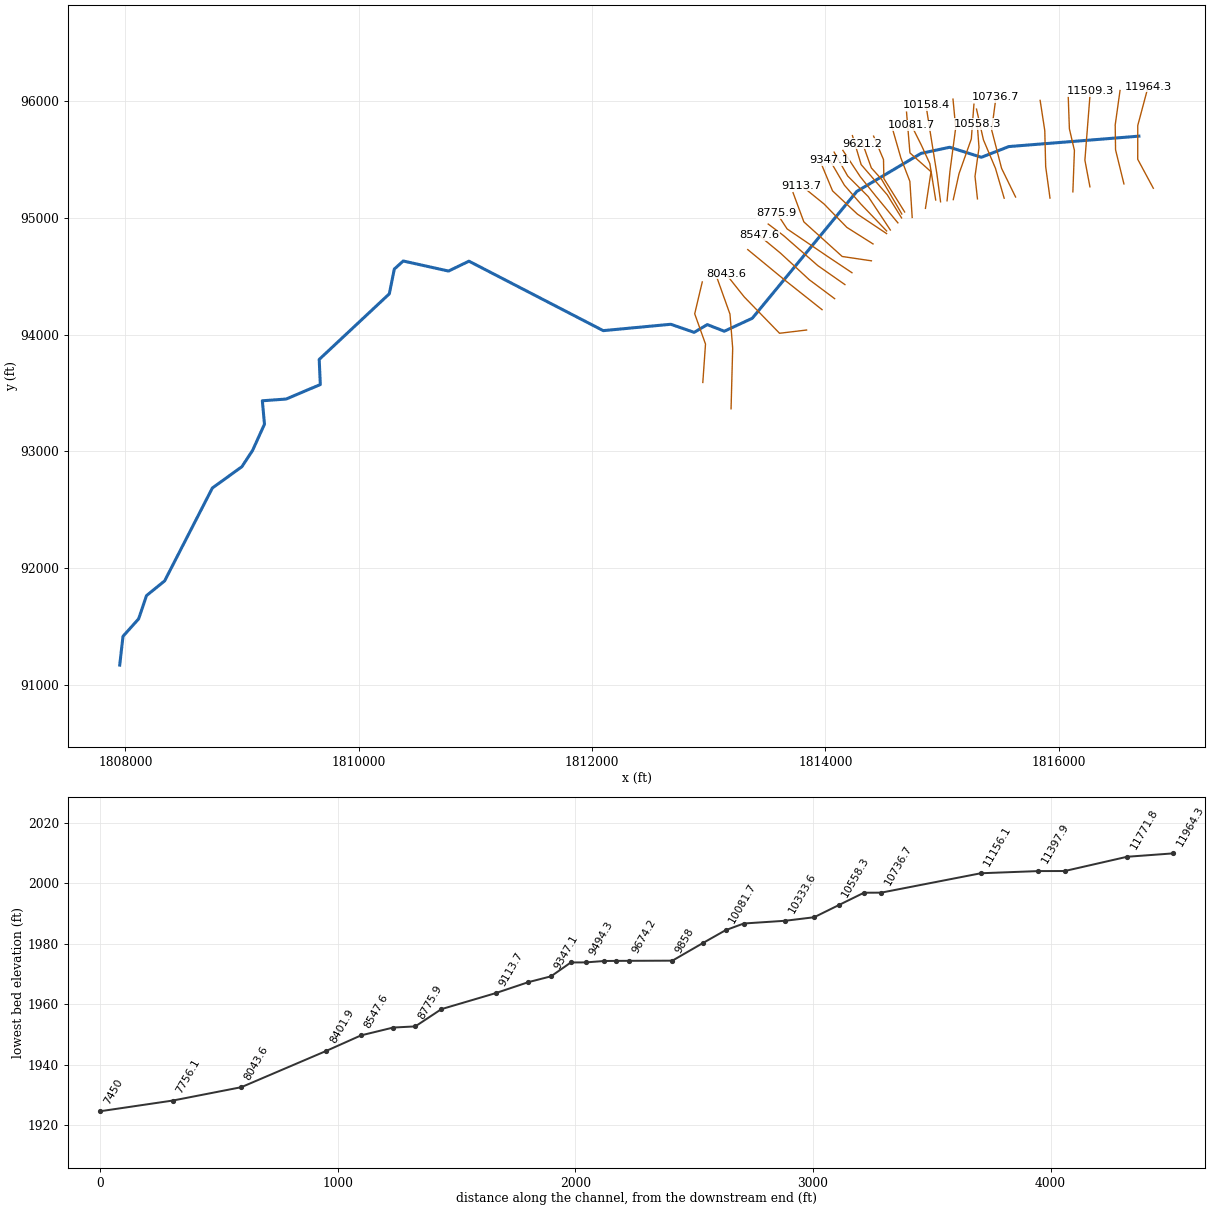
--- North Fork Big Creek.prj (project) ---

Proj Title=NFk Big Ck
Current Plan=p01
Default Exp/Contr=0,0
English Units
Geom File=g01
Flow File=f01
Plan File=p01
BEGIN DESCRIPTION:
END DESCRIPTION:
DSS Export Rating Curves= 0
DSS Export Rating Curve Sorted= 0
DSS Export Volume Flow Curves= 0
DXF OffsetX= 0
DXF OffsetY= 0
DXF ScaleX= 0
DXF ScaleY= 0

--- North Fork Big Creek.p01 (plan) ---

Plan Title=Floodplain
Program Version=4.00
Geom File=g01
Flow File=f01
K Sum by GR=0
Std Step Tol=0.01
Critical Tol=0.01
Num of Std Step Trials=20
Max Error Tol=0.3
Flow Tol Ratio=0.001
Split Flow NTrial=30
Split Flow Tol=0.02
Split Flow Ratio=0.02
Log Output Level=0
Friction Slope Method=1
Unsteady Friction Slope Method=2
Unsteady Bridges Friction Slope Method=1
Global Log Level=0
CheckData=False
Run HTab=0
Run UNet=0
Run PostProcess=0
UNET Theta=0
UNET Theta Warmup=0
UNET ZTol=0
UNET ZSATol=0
UNET MxIter=0
UNET MaxInSteps=0
UNET DtIC=0
UNET DtMin=0
UNET MaxCRTS=0
UNET WFStab=0
UNET SFStab=0
UNET WFX=0
UNET SFX=0
UNET DSS MLevel=0
UNET DZMax Abort=0
UNET Convert EG Bridges=0
UNET Use Existing IB Tables=0
UNET Froude Limit=0
UNET Froude Power=0
Write IC File=0
Echo Input=False
Echo Output=False
Write Detailed=0

--- North Fork Big Creek.f01 (steady flow) ---

Flow Title=NFF Regression Equation
Program Version=4.00
Number of Profiles=1
Profile Names=P100yr
River Rch & RM=North Fork Bi...,Main      ,11964.3
615.8164
River Rch & RM=North Fork Bi...,Main      ,10736.7
634.3150
River Rch & RM=North Fork Bi...,Main      ,10454.7
702.6182
River Rch & RM=North Fork Bi...,Main      ,9251.7
775.0295
River Rch & RM=North Fork Bi...,Main      ,8043.6
818.5379
River Rch & RM=North Fork Bi...,Main      ,7756.1
973.4651
River Rch & RM=North Fork Bi...,Main      ,4761.2
1047.905
River Rch & RM=North Fork Bi...,Main      ,4456.5
1314.458
River Rch & RM=North Fork Bi...,Main      ,295.5
1396.119
Boundary for River Rch & Prof#=North Fork Bi...,Main      ,1
Up Type=0
Dn Type=3
Dn Slope=0.014335

--- North Fork Big Creek.g01 (geometry) ---

Geom Title=USGS 10m DEM
Program Version=4.00

River Reach=NFk Big Ck      ,Main
Reach XY= 30
     1816687.122       95699.806     1815571.868         95610.5
     1815337.338       95518.821     1815065.207       95604.608
     1814819.978       95552.322     1814269.585       95226.532
     1813373.639       94139.859     1813133.564       94028.659
     1812987.752       94085.363     1812875.079       94019.085
     1812674.771       94088.309     1812095.876       94033.773
     1810944.909       94628.845     1810769.639       94544.156
     1810381.543       94630.318     1810304.955       94561.094
     1810262.242       94349.004     1809661.319       93787.111
     1809670.564       93571.877     1809377.971       93447.869
     1809173.806       93432.891     1809192.217       93232.583
     1809090.241       93007.763     1808998.653       92868.356
     1808745.207       92685.419     1808336.491        91890.08
     1808181.105       91764.151     1808113.354        91564.58
     1807979.324       91415.086     1807951.348       91168.527

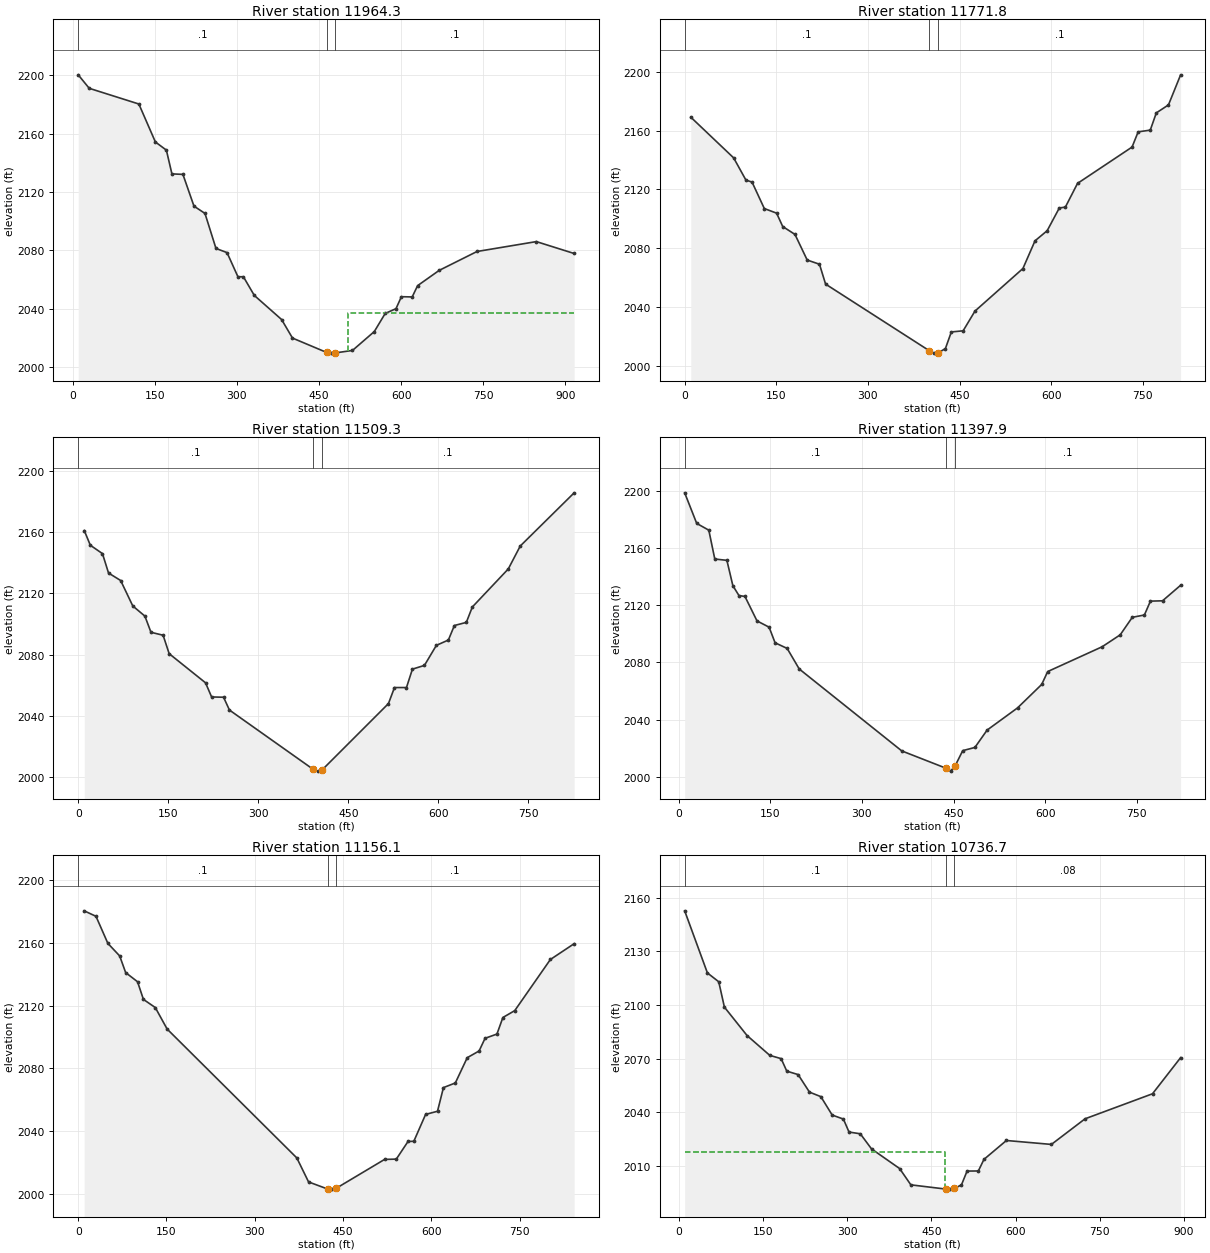
Type RM Length L Ch R = 1 ,11964.3 ,192.1,192.4,192.8
XS GIS Cut Line= 4
     1816810.976       95253.503     1816677.264       95501.777
     1816677.576       95790.807     1816766.509       96124.306
#Sta/Elev= 30
    10.1 2200.16    30.2 2190.94   120.9  2180.2   151.1 2154.22   171.2 2148.64
   181.3  2132.4   201.4 2132.06   221.6 2110.34   241.7 2105.35   261.8 2081.39
     282 2078.55   301.9 2062.04   311.9 2062.04   331.8 2049.28   381.7 2032.77
   401.6 2020.09   463.9 2010.27   471.4 2009.79   478.9 2009.89   511.2 2011.63
   551.1 2024.56     571 2036.94   590.7  2040.2   600.6 2048.39   620.3 2048.23
   630.2 2055.95   669.6 2066.39   738.7 2079.31   847.1 2086.08   916.2 2077.94
#Mann= 3 , 0 , 0
    10.1      .1       0   463.9    .045       0   478.9      .1       0
#XS Ineff= 2 , 0
                          502.66         2037.12
Permanent Ineff=
       F       F
Bank Sta=463.9,478.9
XS Rating Curve= 0 ,0
Exp/Cntr=0.3,0.1

Type RM Length L Ch R = 1 ,11771.8 ,262.9,262.6,262.3
XS GIS Cut Line= 4
     1816558.999       95290.559     1816487.314        95582.82
      1816484.27       95795.927     1816525.649       96090.956
#Sta/Elev= 30
      10 2169.12    80.2 2141.43   100.3 2126.32   110.3 2124.99   130.4 2106.98
   150.5 2103.86   160.5 2094.77   180.6 2089.39   200.6 2071.97   220.7 2069.13
   230.7 2055.62     400 2010.46   407.5 2008.68     415 2008.84   426.9 2011.79
   436.6 2023.09   455.9 2023.85   475.3 2037.27   553.8 2066.21   573.6 2085.04
   593.5 2091.92   613.4 2107.38   623.3 2107.96   643.2 2124.09   732.5  2148.8
   742.5 2159.15   762.3  2160.3   772.2 2172.02   792.1 2177.46     812 2197.91
#Mann= 3 , 0 , 0
       0      .1       0     400    .045       0     415      .1       0
Bank Sta=400,415
XS Rating Curve= 0 ,0
Exp/Cntr=0.3,0.1

Type RM Length L Ch R = 1 ,11509.3 ,106.2,111.4,116.6
XS GIS Cut Line= 3
     1816267.489       95266.038     1816224.439       95494.364
     1816270.944        96085.03
#Sta/Elev= 30
    10.1 2161.05    20.2 2151.47    40.4    2146    50.5 2133.34    70.7 2128.44
    90.9 2111.83   111.1 2105.18   121.2 2094.63   141.4 2092.71   151.5 2080.66
   212.1 2061.64   222.2  2052.4   242.1 2052.23   251.9 2043.86   391.2  2005.2
   398.7 2003.97   406.2 2004.73   516.8 2048.09   526.8 2058.55   546.8 2058.55
   556.7 2070.57   576.7 2073.01   596.6  2086.1   616.6 2089.58   626.6 2099.06
   646.5  2101.1   656.5 2111.15   716.4 2136.01   736.3 2150.96   826.1  2185.7
#Mann= 3 , 0 , 0
       0      .1       0   391.2    .045       0   406.2      .1       0
Bank Sta=391.2,406.2
XS Rating Curve= 0 ,0
Exp/Cntr=0.3,0.1

Type RM Length L Ch R = 1 ,11397.9 ,246.4,241.8,237.1
XS GIS Cut Line= 4
     1816121.399        95222.76     1816134.674       95577.875
     1816091.544       95762.439     1816081.573       96039.193
#Sta/Elev= 30
     9.9 2198.59    29.6  2177.2    49.4 2172.47    59.2  2152.3      79 2151.37
    88.8 2133.63    98.7 2126.78   108.6  2126.1   128.3 2109.01   148.1 2104.63
   157.9 2093.71   177.7 2089.76   197.4 2075.41   365.3 2018.09   437.6    2006
   445.1 2003.95   452.6 2007.59   465.1 2018.28     485 2020.51     505 2032.65
   554.8 2048.16   594.4 2064.58   604.2 2073.59   693.3 2090.92   722.9 2099.27
   742.7 2111.53   762.5 2113.15   772.4 2122.85   792.2 2123.07   821.8 2133.94
#Mann= 3 , 0 , 0
     9.9      .1       0   437.6    .045       0   452.6      .1       0
Bank Sta=437.6,452.6
XS Rating Curve= 0 ,0
Exp/Cntr=0.3,0.1

Type RM Length L Ch R = 1 ,11156.1 ,414.3,419.4,424.6
XS GIS Cut Line= 4
     1815925.299       95169.243     1815888.295       95438.781
     1815880.637       95746.871     1815840.842       96006.304
#Sta/Elev= 30
    10.1 2180.33    30.2 2176.84    50.4 2159.61    70.5  2151.6    80.6 2141.04
   100.8  2135.2   110.8 2123.97     131 2118.77   151.1 2105.09   371.5 2023.07
   391.4 2007.81   423.6 2003.33   431.1 2003.23   438.6 2003.81   520.6 2022.14
   540.5 2022.33   560.4 2033.55   570.3 2033.69   590.3 2050.78   610.5 2052.78
   620.6 2067.84   640.8 2070.79     661 2086.86   681.2 2091.15   691.3 2099.21
   711.5 2101.91   721.6 2112.44   741.8 2116.84   802.3 2149.36   842.7 2159.42
#Mann= 3 , 0 , 0
       0      .1       0   423.6    .045       0   438.6      .1       0
Bank Sta=423.6,438.6
XS Rating Curve= 0 ,0
Exp/Cntr=0.3,0.1

Type RM Length L Ch R = 1 ,10736.7 ,69,72.3,75.6
XS GIS Cut Line= 4
     1815630.198        95178.71      1815510.33       95423.958
     1815425.102       95753.752     1815462.158       96031.668
#Sta/Elev= 30
    10.1 2152.76    50.6 2117.96    70.8 2113.01    80.9 2098.81   121.3 2082.87
   161.8 2071.77     182 2069.94   192.1 2062.93   212.3    2061   232.5 2051.18
   252.8 2048.64     273 2038.33     293 2036.07     303  2028.8   323.1 2027.83
   343.1 2019.37   393.2 2008.35   413.2 1999.22   475.9 1996.83   483.4 1996.82
   490.9 1997.26   503.4 1999.19   513.4 2006.94   533.5 2006.99   543.5 2013.49
   583.5 2024.07   663.7 2021.87   723.7 2036.23   843.9 2050.25     894  2070.5
#Mann= 3 , 0 , 0
    10.1      .1       0   475.9    .045       0   490.9     .08       0
#XS Ineff= 2 , 0
          473.46 2017.43
Permanent Ineff=
       F       F
Bank Sta=475.9,490.9
XS Rating Curve= 0 ,0
Exp/Cntr=0.3,0.1

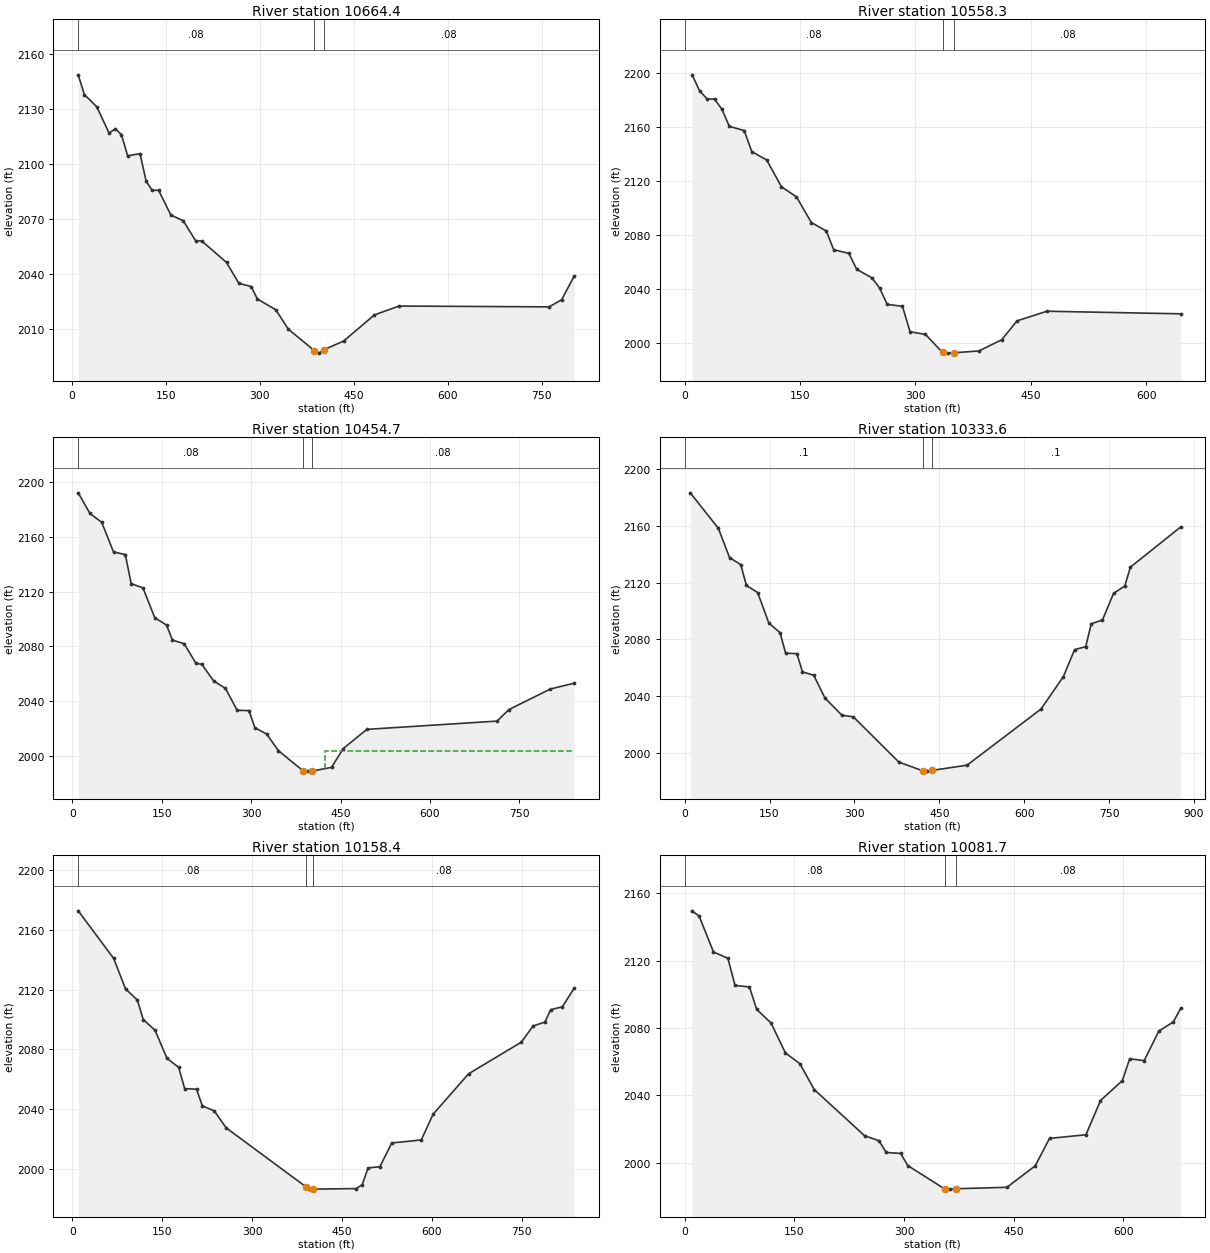
Type RM Length L Ch R = 1 ,10664.4 ,118.5,106.1,93.7
XS GIS Cut Line= 4
     1815532.563       95168.276      1815457.99       95423.959
     1815354.697       95668.524     1815295.408       95931.618
#Sta/Elev= 30
     9.9 2148.79    19.7 2138.01    39.5 2131.35    59.2 2116.94    69.1 2119.34
    78.9 2116.11    88.8 2104.54   108.5 2105.75   118.4  2090.6   128.2 2085.62
   138.1 2085.83   157.8 2072.22   177.6 2069.08   197.3 2058.19   207.2 2058.03
   246.6 2046.32   266.3 2034.91     286 2033.18   295.8 2026.39   325.3 2020.47
     345 2009.98   386.7 1998.21   394.2  1996.8   401.7 1998.59   433.5 2003.38
   482.7 2017.67     522 2022.51   761.6 2022.07   781.5 2025.97   801.5 2038.81
#Mann= 3 , 0 , 0
     9.9     .08       0   386.7    .045       0   401.7     .08       0
Bank Sta=386.7,401.7
XS Rating Curve= 0 ,0
Exp/Cntr=0.3,0.1

Type RM Length L Ch R = 1 ,10558.3 ,108.1,103.5,99
XS GIS Cut Line= 4
     1815303.516       95162.688     1815282.538       95355.304
     1815316.866       95601.318     1815301.609       95803.469
#Sta/Elev= 30
     9.7 2198.67    19.4 2186.84    29.1 2180.86    38.8 2180.72    48.4 2173.22
    58.1 2160.51    77.5 2157.42    87.2 2141.86   106.6 2135.66   125.9 2115.78
   145.3  2108.4   164.7 2089.38   184.1 2083.12   193.8 2069.23   213.6 2066.52
   223.6 2054.78   243.4 2048.46   253.4    2041   263.3 2028.82   283.2 2027.34
   293.1 2008.52     313  2006.6   335.3 1993.21   342.8 1992.71   350.3 1992.98
   382.5 1994.31   412.3 2002.62   432.2 2016.59   471.1 2023.72   644.9  2021.8
#Mann= 3 , 0 , 0
       0     .08       0   335.3    .045       0   350.3     .08       0
Bank Sta=335.3,350.3
XS Rating Curve= 0 ,0
Exp/Cntr=0.3,0.1

Type RM Length L Ch R = 1 ,10454.7 ,116.4,121.1,125.9
XS GIS Cut Line= 4
      1815096.22       95155.963     1815145.309       95377.739
     1815250.942       95675.935     1815273.295       95973.385
#Sta/Elev= 30
     9.9 2192.39    29.6 2177.27    49.4 2170.74    69.1 2149.13    88.9 2147.19
    98.8  2125.9   118.5 2122.82   138.3 2100.96     158 2095.65   167.9 2084.64
   187.6 2081.97   207.4 2067.57   217.3  2066.9     237 2054.73   256.8 2049.28
   276.6  2033.2   296.3 2033.01   306.2 2020.52     326 2015.86   345.8 2003.63
   387.7 1988.72   395.2  1988.7   402.7 1988.76   434.8 1991.45   454.5 2005.22
   494.1 2019.27   712.5 2025.32   732.4 2033.77     802 2048.82   841.8 2053.06
#Mann= 3 , 0 , 0
     9.9     .08       0   387.7    .045       0   402.7     .08       0
#XS Ineff= 2 , 0
                          423.08          2003.3
Permanent Ineff=
       F       F
Bank Sta=387.7,402.7
XS Rating Curve= 0 ,0
Exp/Cntr=0.3,0.1

Type RM Length L Ch R = 1 ,10333.6 ,168.6,175.2,181.8
XS GIS Cut Line= 4
     1815042.968       95146.043     1815068.236       95402.559
     1815117.079       95771.353     1815093.919       96016.845
#Sta/Elev= 30
     9.9 2183.02    59.5 2158.12    79.3 2137.49    99.1  2132.6   109.1 2117.98
   128.9    2113   148.7 2091.59   168.5 2084.79   178.4 2070.39   198.3 2070.05
   208.2 2057.25     228 2054.92   247.8 2038.93   277.9 2026.79     298 2025.69
   378.4  1993.9   421.2 1987.68   428.7 1987.54   436.2 1987.99   499.1 1991.74
   629.8 2031.19   669.2 2053.89     689 2072.84   708.7 2074.99   718.5 2091.03
   738.3 2093.74     758 2112.45   777.7 2117.55   787.6 2130.79   876.4 2159.01
#Mann= 3 , 0 , 0
       0      .1       0   421.2    .045       0   436.2      .1       0
Bank Sta=421.2,436.2
XS Rating Curve= 0 ,0
Exp/Cntr=0.3,0.1

Type RM Length L Ch R = 1 ,10158.4 ,70.6,76.7,82.9
XS GIS Cut Line= 4
     1814987.381       95137.563     1814954.961       95382.271
     1814889.271       95791.842     1814862.323       95965.894
#Sta/Elev= 30
     9.9 2172.59    69.1 2140.78    88.9 2120.42   108.6 2113.01   118.5 2099.89
   138.2  2092.8     158 2074.07   177.7 2067.96   187.6 2053.74   207.4 2053.41
   217.2 2042.21     237 2038.93   256.7 2027.64  390.08 1988.18     395 1986.63
   402.5 1986.64     474    1987   483.9 1989.51   493.8  2000.8   513.5 2001.61
   533.3 2017.48   582.6 2019.48   602.4 2036.72   661.7 2063.73   749.7 2084.85
   769.3 2095.69   788.9  2098.2   798.6 2106.51   818.2  2108.5   837.8 2120.86
#Mann= 3 , 0 , 0
     9.9     .08       0  390.08    .045       0   402.5     .08       0
Bank Sta=390.08,402.5
XS Rating Curve= 0 ,0
Exp/Cntr=0.3,0.1

Type RM Length L Ch R = 1 ,10081.7 ,83.4,93.1,102.9
XS GIS Cut Line= 4
     1814945.606       95153.052       1814895.4       95464.007
     1814822.931       95622.295     1814738.227       95791.515
#Sta/Elev= 30
     9.8 2149.47    19.7  2146.4    39.4 2125.08    59.1  2121.3    68.9 2105.23
    88.6 2104.32    98.4 2091.05   118.1 2082.95   137.8 2065.15   157.5 2058.85
   177.2 2043.47   246.1 2016.08   265.8 2013.09   275.6 2006.15   295.3 2005.59
   305.1 1998.41   355.8 1984.46   363.3 1984.41   370.8 1984.64   440.7 1985.49
   479.4  1998.2     499  2014.5   548.8 2016.65   568.7 2036.96   598.6  2048.8
   608.6 2061.68   628.5 2060.64   648.4  2078.1   668.3 2083.57   678.3 2091.57
#Mann= 3 , 0 , 0
       0     .08       0   355.8    .045       0   370.8     .08       0
Bank Sta=355.8,370.8
XS Rating Curve= 0 ,0
Exp/Cntr=0.3,0.1

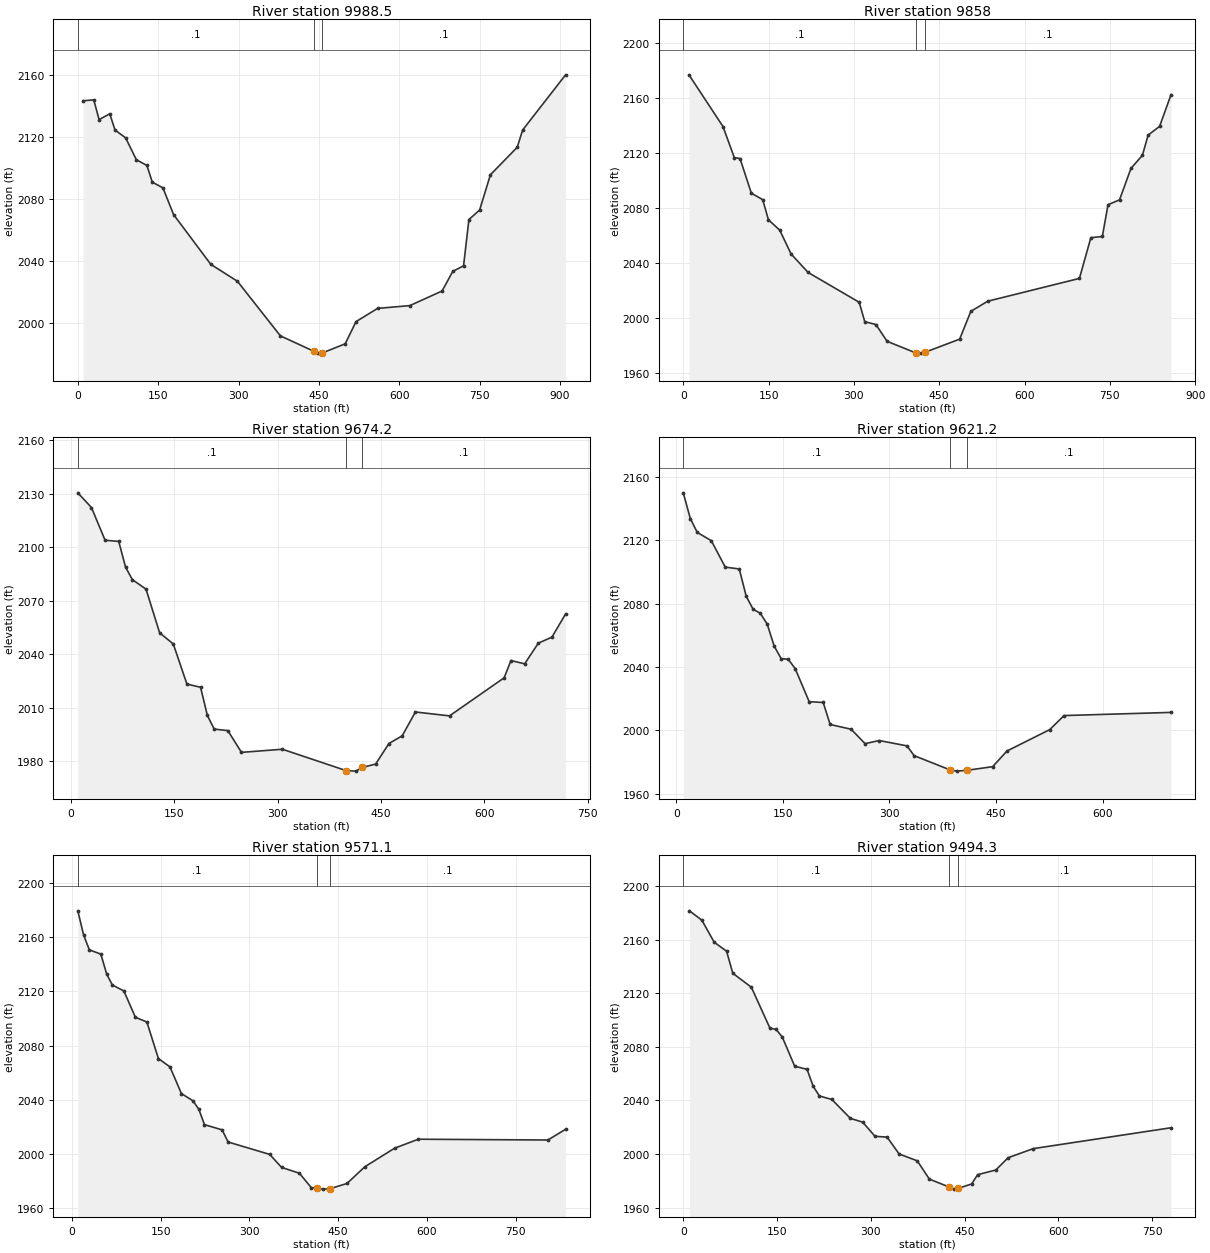
Type RM Length L Ch R = 1 ,9988.5  ,141.6,130.6,119.5
XS GIS Cut Line= 4
     1814857.691       95081.196      1814905.46       95395.237
     1814724.867       95556.057     1814695.573       95905.679
#Sta/Elev= 30
     9.9 2143.24    29.8 2143.82    39.7 2131.08    59.6  2134.8    69.5 2124.33
    89.3 2119.27   109.2 2105.19     129 2101.45     139 2090.69   158.8 2087.01
   178.7 2069.77   248.2  2037.6   297.8  2026.7   378.1 1991.41   441.1 1981.38
   448.6 1980.27   456.1 1980.36     499 1986.28   519.2 2000.61   559.5 2009.16
   619.6 2010.96   679.8 2020.39   699.8 2033.07   719.9 2036.64   729.9 2066.54
   749.9 2072.69     770 2095.45   820.1 2113.22   830.1 2124.32   910.3 2159.99
#Mann= 3 , 0 , 0
       0      .1       0   441.1    .045       0   456.1      .1       0
Bank Sta=441.1,456.1
XS Rating Curve= 0 ,0
Exp/Cntr=0.3,0.1

Type RM Length L Ch R = 1 ,9858    ,192.5,183.7,175
XS GIS Cut Line= 4
     1814744.084       95003.718     1814724.171       95312.369
     1814646.785       95513.922      1814554.91       95833.425
#Sta/Elev= 30
      10 2176.57    69.8 2139.02    89.8 2116.38    99.8 2115.72   119.7 2090.57
   139.7 2085.85   149.7 2071.26   169.6 2063.72   189.6 2046.37   219.5 2032.97
   309.3 2011.31   319.1 1997.21   338.7 1995.11   358.4 1982.93   409.7 1974.36
   417.2 1974.35   424.7 1974.93   485.9 1984.49   505.6 2004.71   535.3 2012.08
   696.5 2028.64   716.6 2058.22   736.8  2059.1   746.8 2082.19     767 2085.72
   787.1 2108.57   807.3 2118.12   817.3 2132.78   837.5 2139.13   857.6 2162.18
#Mann= 3 , 0 , 0
       0      .1       0   409.7    .045       0   424.7      .1       0
Bank Sta=409.7,424.7
XS Rating Curve= 0 ,0
Exp/Cntr=0.3,0.1

Type RM Length L Ch R = 1 ,9674.2  ,35.9,53,70.2
XS GIS Cut Line= 4
     1814679.443       95050.179     1814501.457       95335.936
     1814498.191       95499.226      1814413.28       95700.073
#Sta/Elev= 30
     9.9  2130.5    29.7 2122.25    49.5  2103.9    69.3 2103.22    79.2 2088.83
    89.1 2081.78   108.9 2076.45   128.7 2051.93   148.5 2045.68   168.3 2023.16
   188.1 2021.36     198 2005.53   207.9  1997.9   227.7 1997.04   247.5 1984.83
   306.9 1986.58  399.53 1974.58   413.5  1974.3   423.1 1976.38   442.3 1978.27
   461.5 1989.79   480.8 1994.13     500 2007.49   549.5 2005.31   628.8 2026.68
   638.7 2036.37   658.6 2034.53   678.4 2046.11   698.2 2049.52     718 2062.51
#Mann= 3 , 0 , 0
     9.9      .1       0  399.53    .045       0   423.1      .1       0
Bank Sta=399.53,423.1
XS Rating Curve= 0 ,0
Exp/Cntr=0.3,0.1

Type RM Length L Ch R = 1 ,9621.2  ,50.6,50,49.5
XS GIS Cut Line= 4
     1814655.107       95033.006     1814481.562       95330.511
     1814393.836       95427.773      1814319.46       95635.645
#Sta/Elev= 30
     9.8 2149.99    19.7 2133.78    29.5 2124.99    49.2  2119.8    68.9 2103.08
    88.6 2101.92    98.4 2084.64   108.2 2076.41   118.1 2074.01   127.9 2067.11
   137.8 2053.15   147.6 2045.29   157.5  2044.9   167.3 2038.99     187 2018.11
   206.7 2017.61   216.5 2003.73     246 2000.73   265.7 1991.62   285.4 1993.61
   324.7 1990.22   334.6 1984.07   384.7 1975.15   394.8 1974.28  409.23 1974.81
   445.2  1977.1   465.3 1986.98   525.6 2000.52   545.6 2009.36   696.2 2011.36
#Mann= 3 , 0 , 0
     9.8      .1       0   384.7    .045       0  409.23      .1       0
Bank Sta=384.7,409.23
XS Rating Curve= 0 ,0
Exp/Cntr=0.3,0.1

Type RM Length L Ch R = 1 ,9571.1  ,77.7,76.9,76
XS GIS Cut Line= 4
     1814653.201       94999.231     1814530.046       95197.752
     1814306.491       95456.382     1814231.995       95704.433
#Sta/Elev= 30
     9.7 2179.39    19.5 2161.62    29.2 2150.62    48.7 2147.48    58.4  2132.9
    68.1  2124.7    87.6 2120.32   107.1  2100.9   126.5 2097.43     146 2070.44
   165.5 2064.38   184.9 2044.68   204.4 2039.36   214.2 2033.21   223.9 2021.78
   253.7 2017.92   263.8 2008.98   334.2 1999.84   354.3 1990.26   384.4 1985.95
   404.5 1975.33  413.56 1974.93   424.7 1974.24  435.86 1974.52   464.9 1978.41
     495 1990.72   545.3 2004.39   585.4 2011.03   804.6 2010.45   834.5 2018.35
#Mann= 3 , 0 , 0
     9.7      .1       0  413.56    .045       0  435.86      .1       0
Bank Sta=413.56,435.86
XS Rating Curve= 0 ,0
Exp/Cntr=0.3,0.1

Type RM Length L Ch R = 1 ,9494.3  ,61.2,63.7,66.2
XS GIS Cut Line= 4
     1814621.287       94957.254     1814432.114       95186.253
      1814299.36       95352.195     1814150.013       95577.875
#Sta/Elev= 30
     9.9 2181.42    29.7 2174.45    49.5 2157.99    69.3 2151.29    79.2 2134.86
   108.9 2124.41   138.6 2093.92   148.5 2092.91   158.4 2087.24   178.2 2065.49
     198 2063.15   207.9 2050.43   217.8 2043.27   237.6  2040.7   267.3 2026.58
   287.1 2023.71   306.7 2013.18     326  2012.6   345.3 1999.99   374.3 1994.88
   393.6 1981.25   424.8 1975.44   432.3 1973.78   439.8 1974.34   461.2 1977.62
   470.9 1984.58   499.9 1988.05   519.6 1997.21   559.7 2003.99   780.2 2019.58
#Mann= 3 , 0 , 0
       0      .1       0   424.8    .045       0   439.8      .1       0
Bank Sta=424.8,439.8
XS Rating Curve= 0 ,0
Exp/Cntr=0.3,0.1

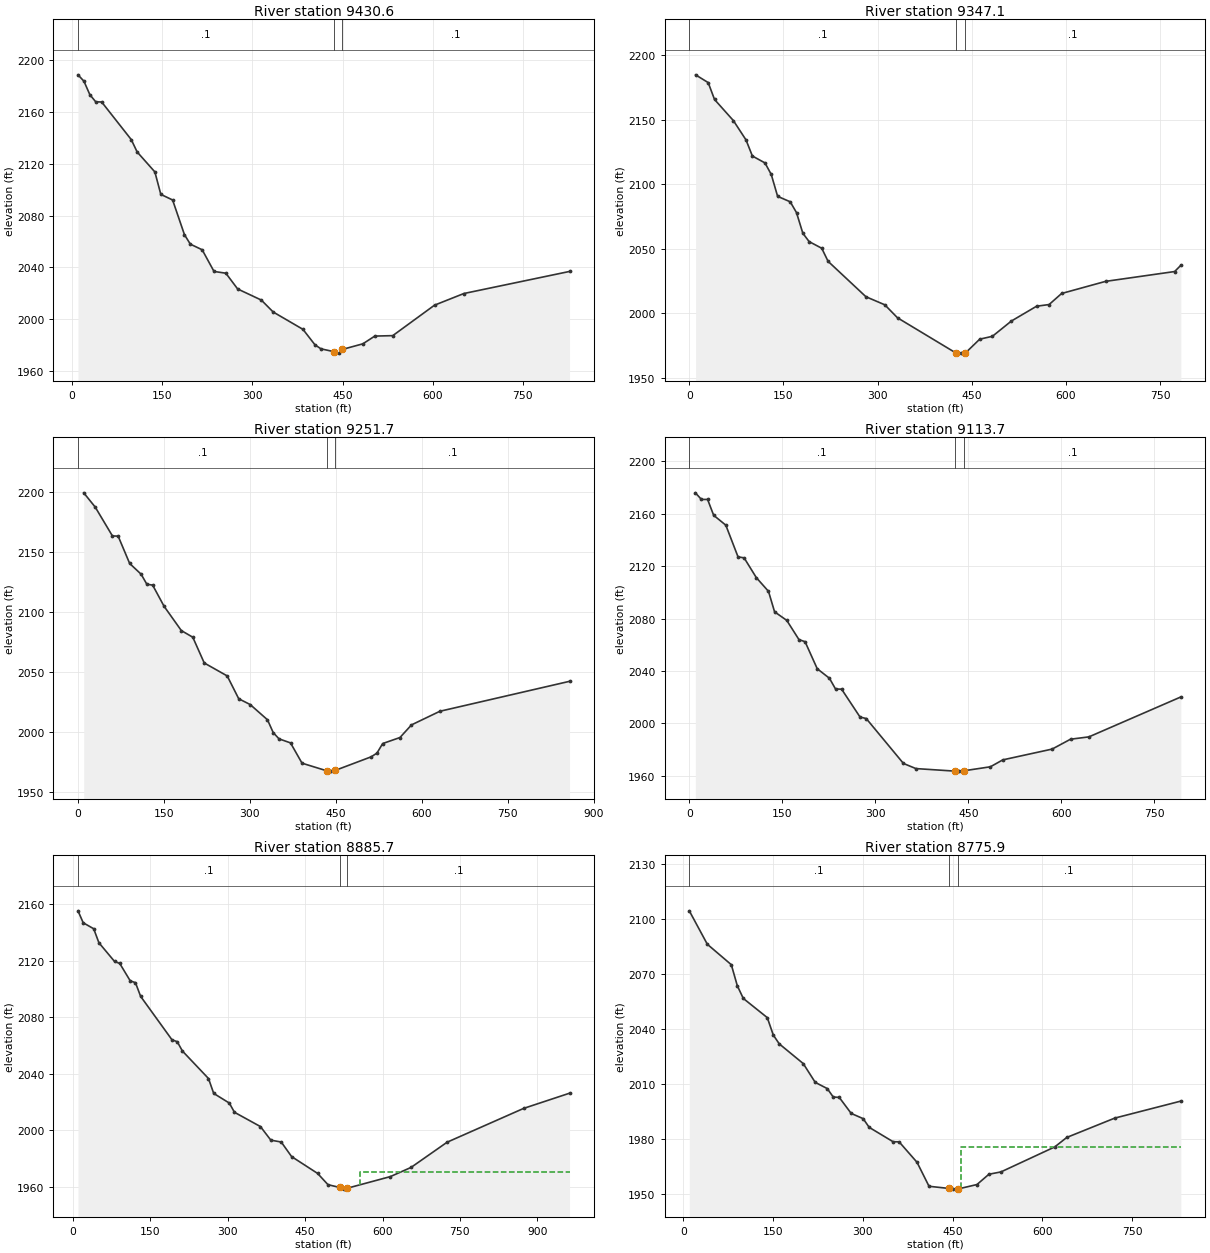
Type RM Length L Ch R = 1 ,9430.6  ,85,83.5,82
XS GIS Cut Line= 4
     1814556.615       94895.918     1814366.706       95183.098
     1814190.693       95359.111     1814074.894       95562.916
#Sta/Elev= 30
     9.8 2188.71    19.7 2183.78    29.5 2173.39    39.3 2167.87    49.2 2167.73
    98.4  2138.7   108.2 2129.15   137.7 2113.72   147.6 2096.38   167.2 2092.05
   186.9 2065.28   196.7 2057.93   216.4 2053.59   236.1 2036.85   255.8 2035.49
   275.4 2023.33   314.8 2014.75   334.5 2005.54   384.1 1992.12     404 1980.22
     414 1977.08   436.4 1974.82   443.9 1973.76   449.4  1976.6   483.7 1980.94
   503.6 1986.92   533.5 1987.27     603 2010.81   651.8  2019.8   827.6 2036.85
#Mann= 3 , 0 , 0
     9.8      .1       0   436.4    .045       0   449.4      .1       0
Bank Sta=436.4,449.4
XS Rating Curve= 0 ,0
Exp/Cntr=0.3,0.1

Type RM Length L Ch R = 1 ,9347.1  ,93.1,95.4,97.6
XS GIS Cut Line= 4
     1814525.041       94887.558     1814302.679       95119.877
     1814163.288        95279.18     1814037.173       95494.905
#Sta/Elev= 30
      10 2184.93    30.1  2178.9    40.2 2165.82    70.3 2149.41    90.4 2134.43
   100.5 2121.99   120.6 2116.62   130.6 2107.66   140.7 2090.73   160.8  2086.5
   170.8  2078.1   180.9  2062.1   190.9 2055.65     211 2050.49   221.1 2040.35
   281.4  2012.9   311.5 2006.64   331.7 1996.57     425 1969.22   432.5 1969.18
     440 1969.34   462.7    1980   482.9 1982.22   513.1 1994.05   553.3 2005.55
   573.2 2006.84   593.2 2015.43   663.2 2024.81   773.2 2032.43   783.1 2037.26
#Mann= 3 , 0 , 0
       0      .1       0     425    .045       0     440      .1       0
Bank Sta=425,440
XS Rating Curve= 0 ,0
Exp/Cntr=0.3,0.1

Type RM Length L Ch R = 1 ,9251.7  ,139.1,138.1,137.1
XS GIS Cut Line= 4
     1814524.426       94865.312     1814274.302       95032.062
     1814061.233       95231.235      1813959.33       95476.727
#Sta/Elev= 30
      10 2199.11    30.1 2187.21    60.1  2163.2    70.1 2163.03    90.2 2140.26
   110.2 2131.31   120.2 2122.96   130.3 2122.23   150.3 2104.57   180.4 2084.35
   200.4 2078.81   220.4 2057.36   260.5 2046.56   280.6 2027.54   300.6 2022.72
   330.8 2010.03   340.8 1999.36   350.9 1994.15     371 1990.78   391.1 1973.87
   433.9 1967.57   441.4 1967.25   448.9 1967.83   511.8 1979.17   521.9 1982.25
   531.9 1990.23   562.1 1995.25   582.2 2005.77   631.7 2017.11   858.1 2042.07
#Mann= 3 , 0 , 0
       0      .1       0   433.9    .045       0   448.9      .1       0
Bank Sta=433.9,448.9
XS Rating Curve= 0 ,0
Exp/Cntr=0.3,0.1

Type RM Length L Ch R = 1 ,9113.7  ,226.6,228,229.4
XS GIS Cut Line= 4
     1814408.571       94776.378     1814184.319        94918.05
     1813988.531       95118.632     1813796.661       95274.202
#Sta/Elev= 30
     9.8 2176.01    19.6 2170.96    29.5 2170.96    39.3 2158.86    58.9 2151.32
    78.6 2127.12    88.4 2126.38   108.1 2111.28   127.7 2100.82   137.5 2085.21
   157.2 2078.64   176.8 2064.01   186.7 2062.38   206.3 2041.75     226 2034.48
   235.8 2026.29   245.6 2026.16   275.3  2004.9   285.3 2003.75   345.3 1969.47
   365.4 1965.55   427.9 1963.63   435.4 1963.61   442.9 1963.88   485.5 1966.92
   505.5  1972.2   585.1 1980.44   614.7 1987.96   644.4 1989.76   792.6 2020.22
#Mann= 3 , 0 , 0
       0      .1       0   427.9    .045       0   442.9      .1       0
Bank Sta=427.9,442.9
XS Rating Curve= 0 ,0
Exp/Cntr=0.3,0.1

Type RM Length L Ch R = 1 ,8885.7  ,106.6,109.8,112.9
XS GIS Cut Line= 4
     1814394.498       94631.898     1814144.373       94668.954
     1813815.506       94965.397     1813722.868       95215.522
#Sta/Elev= 30
    10.1 2155.47    20.2    2147    40.5 2142.78    50.6 2132.87    80.9 2119.61
      91 2118.18   111.3 2105.86   121.4 2104.58   131.5 2094.84   192.2  2064.1
   202.3 2062.78   212.4 2056.16   262.9 2036.68     273 2026.14   303.2  2019.3
   313.2 2012.77   363.5 2002.65   383.7 1993.01   403.8 1991.71   423.9 1981.38
   474.2 1969.48   494.4 1961.48     517 1959.52   524.5 1958.33     532    1959
   615.1 1967.19   655.4 1973.73   725.2 1991.58   873.4 2015.52   962.3 2026.28
#Mann= 3 , 0 , 0
    10.1      .1       0     517    .045       0     532      .1       0
#XS Ineff= 2 , 0
                           557.2         1970.71
Permanent Ineff=
       F       F
Bank Sta=517,532
XS Rating Curve= 0 ,0
Exp/Cntr=0.3,0.1

Type RM Length L Ch R = 1 ,8775.9  ,95.8,93.1,90.4
XS GIS Cut Line= 4
     1814227.748       94529.996     1814019.311       94668.954
     1813671.917       94905.182      1813583.91       95039.508
#Sta/Elev= 30
      10 2104.31    40.1  2086.1    80.2 2074.94    90.2 2063.49   100.2 2056.57
   140.3  2046.1   150.3 2036.62   160.3  2031.8   200.4 2021.05   220.4 2010.81
   240.5 2007.43   250.5 2002.82   260.5 2002.63   280.5 1993.89   300.5 1991.04
   310.5 1986.31   350.5 1978.46   360.5 1978.42   390.5 1967.24   410.5 1954.18
   443.1 1953.03   450.6 1952.63   458.1 1952.66   490.6 1955.13   510.6 1960.75
   530.6    1962   620.6 1975.64   640.6 1980.79   720.8 1991.34   831.2 2000.61
#Mann= 3 , 0 , 0
      10      .1       0   443.1    .045       0   458.1      .1       0
#XS Ineff= 2 , 0
                          464.31         1975.45
Permanent Ineff=
       F       F
Bank Sta=443.1,458.1
XS Rating Curve= 0 ,0
Exp/Cntr=0.3,0.1

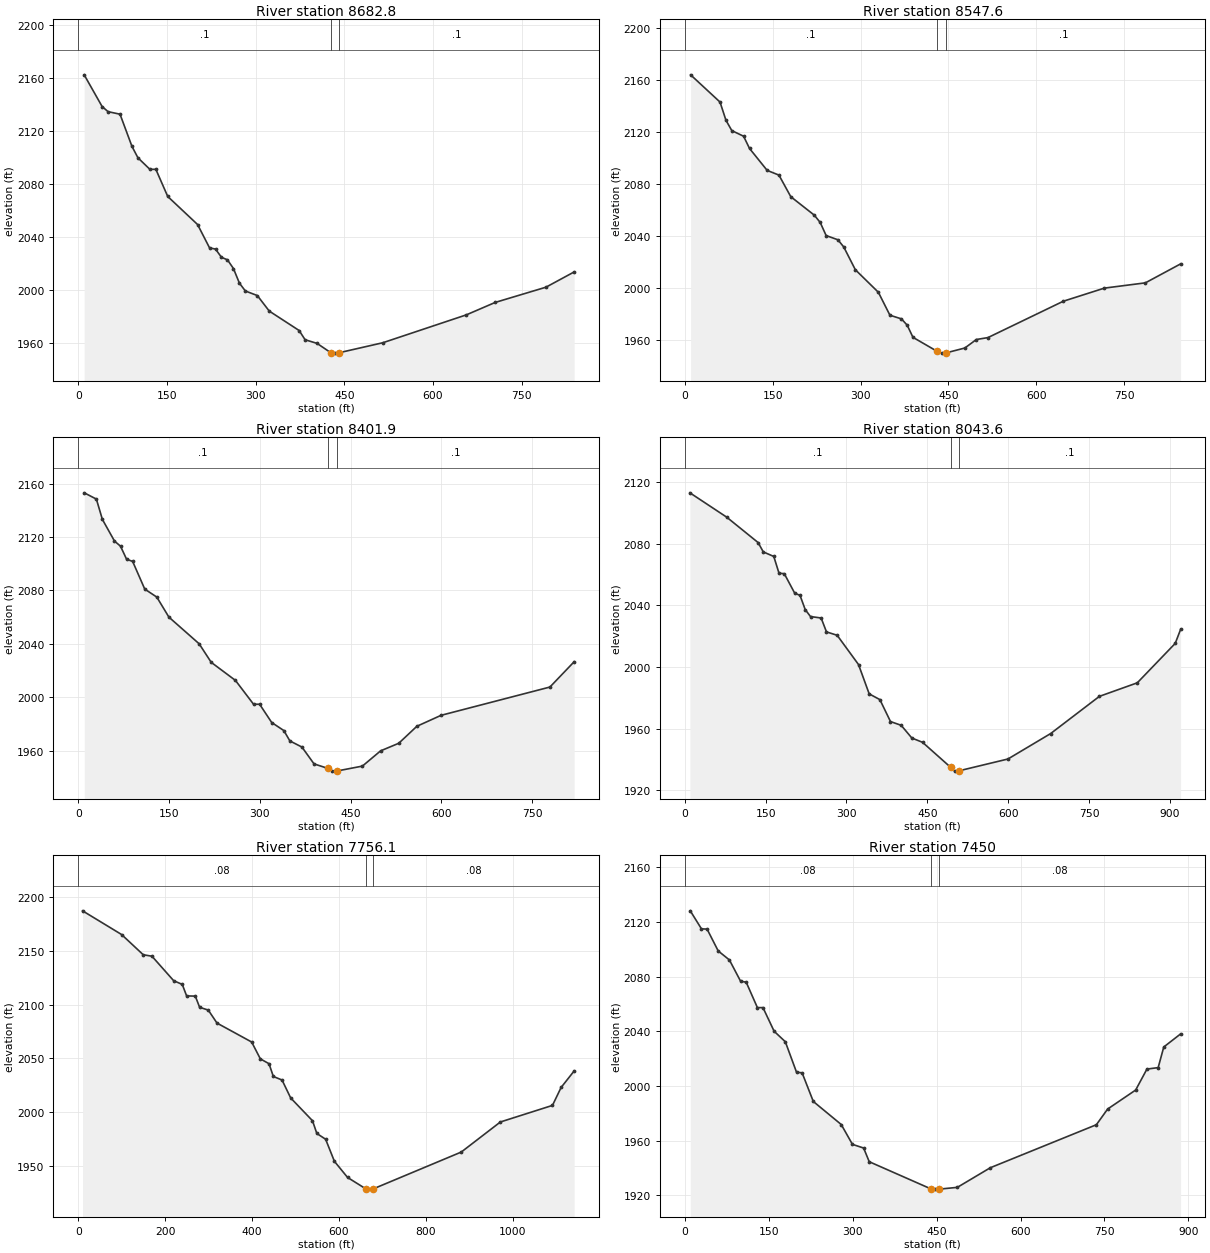
Type RM Length L Ch R = 1 ,8682.8  ,135.9,135.3,134.6
XS GIS Cut Line= 4
     1814167.533       94428.093     1813935.937       94590.211
     1813639.493       94849.599     1813509.799        94946.87
#Sta/Elev= 30
    10.1 2162.26    40.4 2138.35    50.5 2134.46    70.7 2132.55    90.9 2108.26
     101 2099.65   121.2 2090.95   131.3 2090.95   151.4 2070.46   201.9 2049.28
   222.1 2031.68   232.2 2030.75   242.3 2024.54   252.4 2022.66   262.5  2016.1
   272.6 2005.07   282.7 1999.14   302.9  1995.7   323.1 1983.97   373.6 1969.32
   383.7 1962.35   403.9 1959.61   426.7 1952.71   434.2 1952.25   441.7  1952.6
     515 1960.07   656.4 1981.13   705.2 1990.51     791    2002   838.7 2013.52
#Mann= 3 , 0 , 0
       0      .1       0   426.7    .045       0   441.7      .1       0
Bank Sta=426.7,441.7
XS Rating Curve= 0 ,0
Exp/Cntr=0.3,0.1

Type RM Length L Ch R = 1 ,8547.6  ,144.2,145.7,147
XS GIS Cut Line= 4
     1814079.526       94307.663     1813861.826       94469.781
     1813616.333       94696.745     1813431.056       94849.599
#Sta/Elev= 30
    10.1 2164.14    60.3 2143.14    70.4 2129.13    80.4 2121.15   100.5 2116.82
   110.6  2107.4   140.7 2090.49   160.8 2086.86     181 2070.22   221.2 2055.96
   231.2 2050.36   241.3 2040.27   261.4 2037.01   271.4 2031.44   291.1 2013.95
   330.4 1996.56   350.1 1978.88   369.8 1976.05   379.6 1971.18   389.4 1961.84
   431.1 1950.93   438.6 1949.66   446.1 1949.88   477.9  1953.6   497.6 1960.16
   517.3 1961.63   645.8 1989.64   715.9 1999.76   785.9 2003.82     846 2018.44
#Mann= 3 , 0 , 0
       0      .1       0   431.1    .045       0   446.1      .1       0
Bank Sta=431.1,446.1
XS Rating Curve= 0 ,0
Exp/Cntr=0.3,0.1

Type RM Length L Ch R = 1 ,8401.9  ,360.6,358.3,356.2
XS GIS Cut Line= 3
      1813971.65       94213.281     1813650.819       94467.734
     1813334.525       94727.953
#Sta/Elev= 30
      10 2153.05      30 2148.35    39.9 2133.15    59.9 2116.93    69.9 2113.04
    79.9 2103.29    89.9 2101.66   109.9 2080.93   129.8 2074.93   149.8 2059.92
   199.7 2039.97   219.7 2026.04   259.7 2012.51   289.6 1994.66   299.6 1994.66
   319.6 1980.96   339.6 1974.95   349.6 1967.17   369.5 1962.58   389.5 1949.96
     412 1946.66   419.5 1944.55     427 1944.62   469.4 1948.32   499.4 1959.73
   529.4 1965.42   559.3 1978.14   599.3 1986.36   779.1 2007.55   819.1 2026.51
#Mann= 3 , 0 , 0
       0      .1       0     412    .045       0     427      .1       0
Bank Sta=412,427
XS Rating Curve= 0 ,0
Exp/Cntr=0.3,0.1

Type RM Length L Ch R = 1 ,8043.6  ,303.2,287.4,271.6
XS GIS Cut Line= 4
     1813838.666       94039.011     1813607.069        94011.22
     1813303.711       94323.357     1813147.425       94519.724
#Sta/Elev= 30
     9.7 2112.89    77.8 2097.15   136.1 2080.67   145.8 2074.59   165.2 2071.66
   174.9 2060.79   184.7 2060.49   204.1 2047.79   213.8 2046.48   223.5 2037.21
   233.3 2032.71     253 2031.77   262.9 2022.77   282.7 2020.58   322.3 2001.61
   342.1  1982.6   361.9 1978.89   381.6 1964.66   401.4 1962.23   421.2 1953.98
     441 1951.22   492.9 1935.08   500.4 1932.54   507.9 1932.69   599.3 1940.39
   678.6  1956.9   768.9 1980.99   839.2 1989.77   909.5 2015.32   919.5  2024.4
#Mann= 3 , 0 , 0
       0      .1       0   492.9    .045       0   507.9      .1       0
Bank Sta=492.9,507.9
XS Rating Curve= 0 ,0
Exp/Cntr=0.3,0.1

Type RM Length L Ch R = 1 ,7756.1  ,298.1,306.2,313.5
XS GIS Cut Line= 4
      1813191.53       93364.382     1813205.425       93883.158
     1813182.266        94174.97     1813071.238       94485.442
#Sta/Elev= 30
      10 2187.49    99.8 2165.41   149.7 2146.54   169.7  2145.2   219.6 2122.41
   239.5  2118.9   249.5 2108.21   269.5    2108   279.4 2097.61   299.4 2094.96
   319.4 2082.88   399.2 2065.23   419.2 2049.52   439.1 2045.03   449.1 2033.11
   469.1 2029.82     489 2013.11   539.2 1991.87   549.2 1979.99   569.4 1974.64
   589.6 1954.08   619.9 1939.03   662.9 1928.15   670.4 1928.14   677.9 1928.19
   881.6 1962.69   971.6 1990.71  1091.5 2006.17  1111.4 2022.89  1141.4 2038.28
#Mann= 3 , 0 , 0
       0     .08       0   662.9    .045       0   677.9     .08       0
Bank Sta=662.9,677.9
XS Rating Curve= 0 ,0
Exp/Cntr=0.3,0.1

Type RM Length L Ch R = 1 ,7450    ,248.5,233.8,218.9
XS GIS Cut Line= 4
     1812949.335       93589.714     1812972.495       93918.581
     1812879.856       94177.969     1812944.703       94451.253
#Sta/Elev= 30
      10 2128.18      30 2114.98      40 2114.83    59.9 2098.83    79.9 2092.25
    99.9 2076.69   109.9 2075.98   129.9  2057.4   139.9 2057.37   159.8 2040.09
   179.8 2032.41   199.8 2010.14   209.8 2009.66   229.8 1988.72   279.7 1971.86
   299.7 1957.35   319.7 1954.66   329.7 1944.65   440.2 1924.73   447.7  1924.6
   455.2 1924.61   487.1 1925.89   546.1 1940.26   735.5 1971.71   755.6 1983.18
   805.7 1997.09   825.8 2012.41   845.9 2013.49   855.9 2028.57     886 2038.14
#Mann= 3 , 0 , 0
       0     .08       0   440.2    .045       0   455.2     .08       0
Bank Sta=440.2,455.2
XS Rating Curve= 0 ,0
Exp/Cntr=0.3,0.1