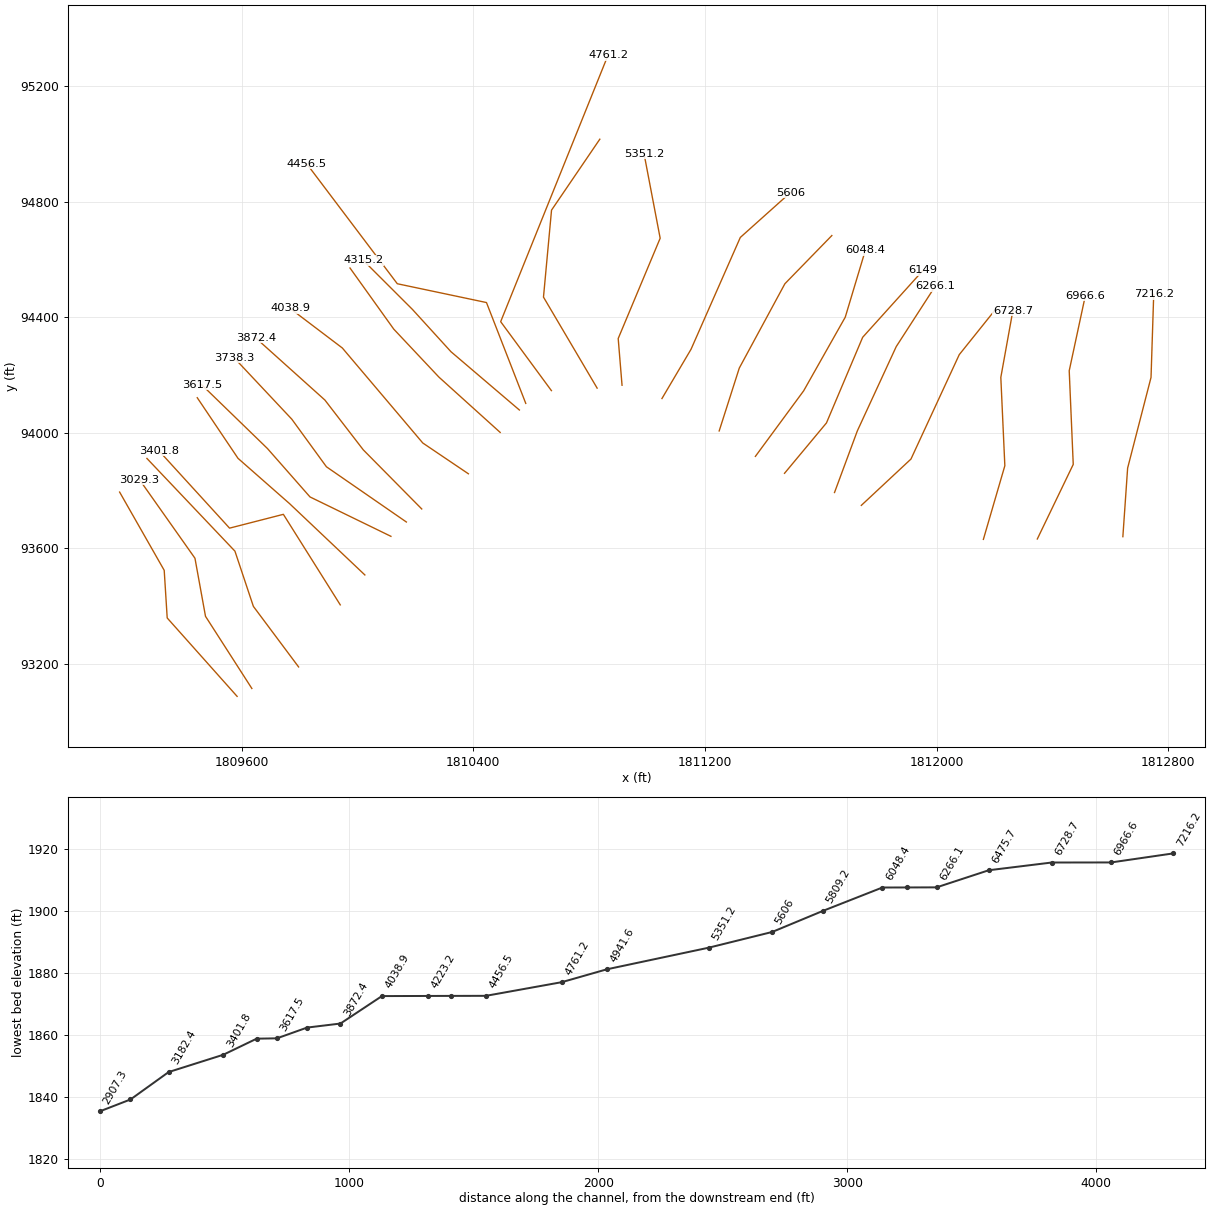
HEC-RAS study North Fork Big Creek.prj: NFk Big Ck

--- North Fork Big Creek.g01 (geometry) --- (continued)

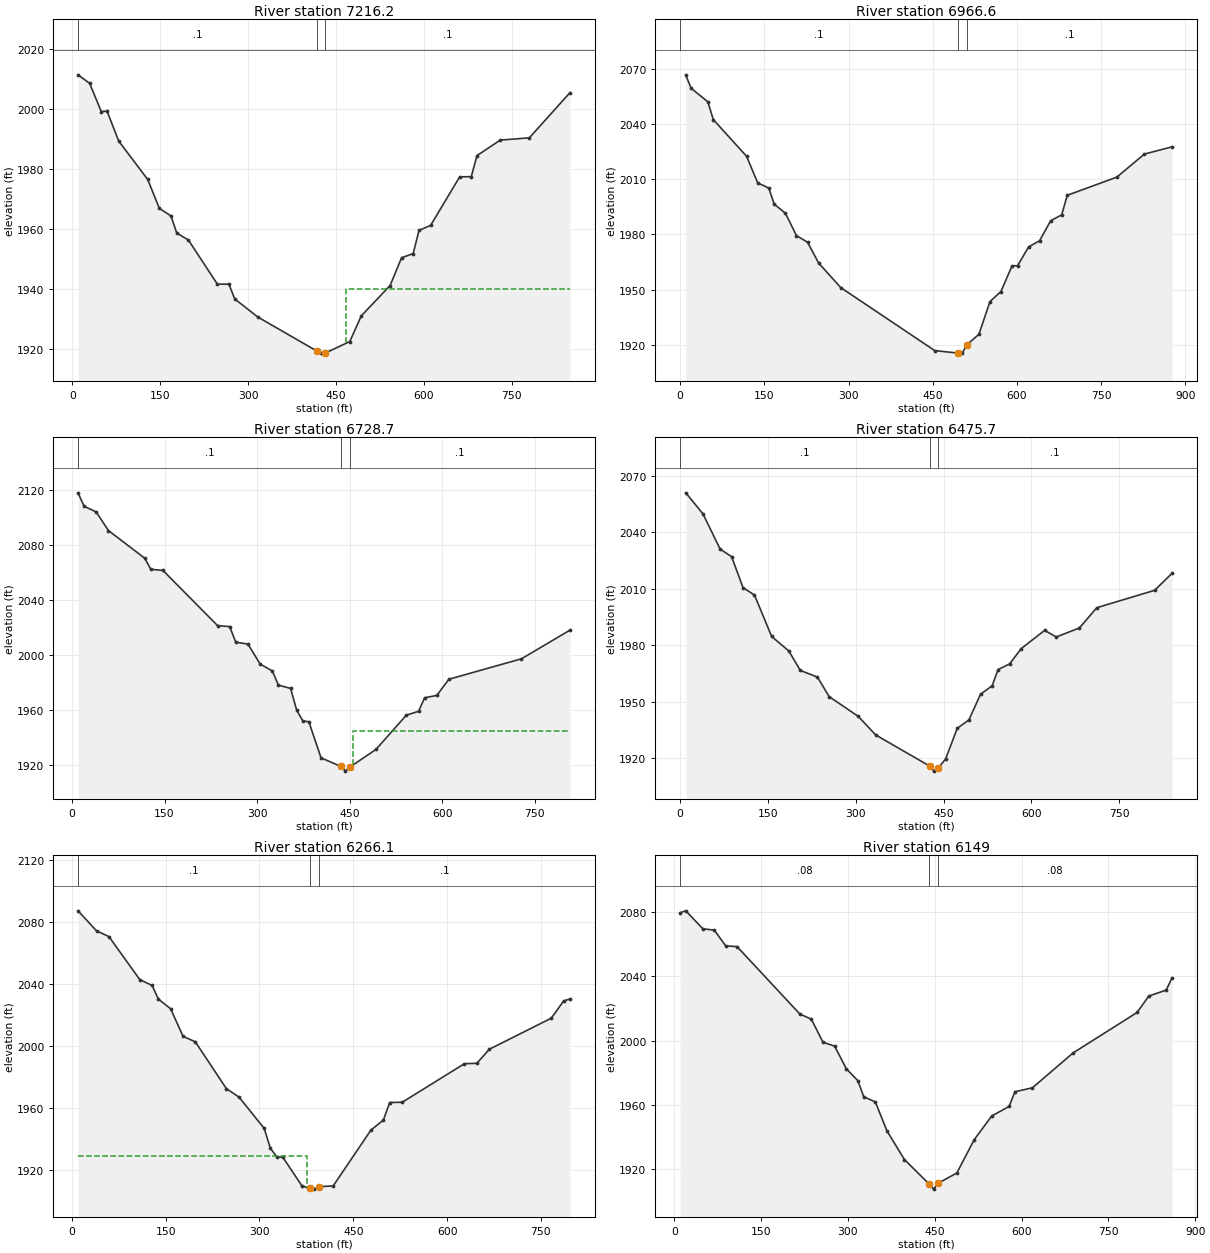
Type RM Length L Ch R = 1 ,7216.2  ,242.9,249.6,256.3
XS GIS Cut Line= 4
     1812643.628       93640.665     1812660.067       93878.005
     1812740.898       94191.865     1812750.162       94479.045
#Sta/Elev= 30
     9.9 2011.28    29.7 2008.45    49.6 1999.03    59.5 1999.17    79.3 1989.21
   128.9 1976.39   148.7 1966.76   168.5 1964.26   178.4 1958.54   198.3 1956.21
   247.7 1941.49   267.4 1941.52   277.2  1936.6   316.5 1930.57     417 1919.25
   424.5 1918.51     432 1918.55   473.6 1922.37   493.3 1930.94   542.4 1941.04
     562 1950.31   581.8 1951.69   591.7 1959.42   611.5 1961.09   661.1 1977.25
   680.9 1977.35   690.8 1984.37   730.4 1989.52     780 1990.27   849.3 2005.34
#Mann= 3 , 0 , 0
     9.9      .1       0     417    .045       0     432      .1       0
#XS Ineff= 2 , 0
                          466.59         1939.89
Permanent Ineff=
       F       F
Bank Sta=417,432
XS Rating Curve= 0 ,0
Exp/Cntr=0.3,0.1

Type RM Length L Ch R = 1 ,6966.6  ,238.1,237.9,237.7
XS GIS Cut Line= 4
     1812348.176       93632.741     1812472.247       93890.789
     1812458.351       94215.025     1812513.934       94474.413
#Sta/Elev= 30
     9.9 2066.62    19.7 2059.33    49.4 2051.98    59.2 2042.32   118.5 2022.38
   138.2 2008.02     158 2005.14   167.8 1996.39   187.6  1991.5   207.3 1979.38
   227.1 1975.75   246.8 1964.46   286.3 1951.13   453.5 1916.98   495.2 1915.61
   502.7  1915.6   510.2 1919.96   532.2 1925.84   551.9 1943.58   571.5 1949.04
   591.2    1963     601 1962.99   620.7 1973.24   640.3 1976.62     660 1987.45
   679.6 1990.63   689.5 2001.24   777.9 2011.12     827 2023.64   876.1 2027.54
#Mann= 3 , 0 , 0
       0      .1       0   495.2    .045       0   510.2      .1       0
Bank Sta=495.2,510.2
XS Rating Curve= 0 ,0
Exp/Cntr=0.3,0.1

Type RM Length L Ch R = 1 ,6728.7  ,263.8,253.1,242.3
XS GIS Cut Line= 4
     1812161.907       93631.401     1812236.018       93886.157
     1812222.122       94191.865      1812263.81       94423.461
#Sta/Elev= 30
     9.8 2117.84    19.7 2108.07    39.3 2103.94      59 2090.46   117.9  2070.3
   127.7 2062.27   147.4 2061.44   235.8 2021.38   255.5 2020.58   265.3 2009.37
   285.1 2007.87   304.8  1993.4   324.5 1988.44   334.4 1978.11   354.2 1975.69
     364 1959.87   373.9 1952.14   383.8 1951.42   403.5 1925.22   435.5 1919.05
     443 1915.58   450.5 1918.61   492.4 1931.33   541.7 1956.27   561.5 1959.04
   571.3 1968.92     591  1970.6   610.6 1982.36   728.2 1997.22   806.7 2018.04
#Mann= 3 , 0 , 0
     9.8      .1       0   435.5    .045       0   450.5      .1       0
#XS Ineff= 2 , 0
                          455.73         1944.54
Permanent Ineff=
       F       F
Bank Sta=435.5,450.5
XS Rating Curve= 0 ,0
Exp/Cntr=0.3,0.1

Type RM Length L Ch R = 1 ,6475.7  ,209.5,209.5,209.6
XS GIS Cut Line= 4
     1811740.393        93749.03     1811911.783       93909.317
     1812078.533       94270.608     1812208.227       94432.725
#Sta/Elev= 30
     9.8 2061.09    39.1 2049.89    68.4 2031.17      88 2027.12   107.6 2010.62
   127.1 2006.74   156.4 1984.71   185.8 1976.95   205.3 1966.66   234.7 1963.08
   254.6 1952.71   304.3 1942.22   334.1 1932.33   426.1 1915.82   433.6 1913.09
   441.1 1914.79   453.5 1919.55   473.4 1935.84   493.3 1940.34   513.2 1954.01
   533.1  1958.5     543 1967.05   562.9 1970.15   582.8 1978.28   622.6 1987.94
   642.5 1984.44     682 1989.22   711.7    2000   810.5 2009.24   840.2 2018.29
#Mann= 3 , 0 , 0
       0      .1       0   426.1    .045       0   441.1      .1       0
Bank Sta=426.1,441.1
XS Rating Curve= 0 ,0
Exp/Cntr=0.3,0.1

Type RM Length L Ch R = 1 ,6266.1  ,116.4,117.1,117.9
XS GIS Cut Line= 4
     1811647.763       93793.519     1811726.506       94006.588
     1811860.832       94298.399     1811995.158       94506.836
#Sta/Elev= 30
     9.9 2087.09    39.5 2074.19    59.3 2070.49   108.6 2042.75   128.4 2038.94
   138.3 2030.17     158 2023.91   177.8 2006.14   197.5 2002.57   247.2 1972.35
   267.3 1966.94   307.5 1946.81   317.5 1933.88   327.5  1928.6   337.6 1927.99
   367.7 1909.81   380.3 1908.02   387.8 1907.58   395.3 1909.15   417.9 1909.67
   478.1 1945.61   498.2 1952.19   508.2 1963.44   528.3 1963.62   627.7 1988.49
   647.6 1988.73   667.4 1997.78   766.6 2017.85   786.4 2029.02   796.4  2030.2
#Mann= 3 , 0 , 0
     9.9      .1       0   380.3    .045       0   395.3      .1       0
#XS Ineff= 2 , 0
          376.06 1929.04
Permanent Ineff=
       F       F
Bank Sta=380.3,395.3
XS Rating Curve= 0 ,0
Exp/Cntr=0.3,0.1

Type RM Length L Ch R = 1 ,6149    ,103.4,100.6,97.8
XS GIS Cut Line= 4
     1811475.118       93860.013     1811619.971       94034.379
     1811745.034       94330.823      1811953.47       94562.419
#Sta/Elev= 30
     9.9 2079.63    19.7  2080.8    49.3 2069.61      69 2068.79    88.7    2059
   108.4 2058.52   216.8 2016.57   236.7 2013.36   256.8 1998.99     277 1996.57
   297.1 1982.53   317.2 1975.04   327.2 1965.09   347.3 1961.86   367.4 1943.81
   397.6 1925.96   440.4 1910.71   447.9 1907.55   455.4 1911.15   488.1 1917.56
   518.3 1938.39   548.4 1953.05   578.6 1959.07   588.6 1968.18   618.8 1970.63
   689.1 1992.35   799.7 2017.54   819.8 2027.71     850 2031.49     860 2039.01
#Mann= 3 , 0 , 0
     9.9     .08       0   440.4    .045       0   455.4     .08       0
Bank Sta=440.4,455.4
XS Rating Curve= 0 ,0
Exp/Cntr=0.3,0.1

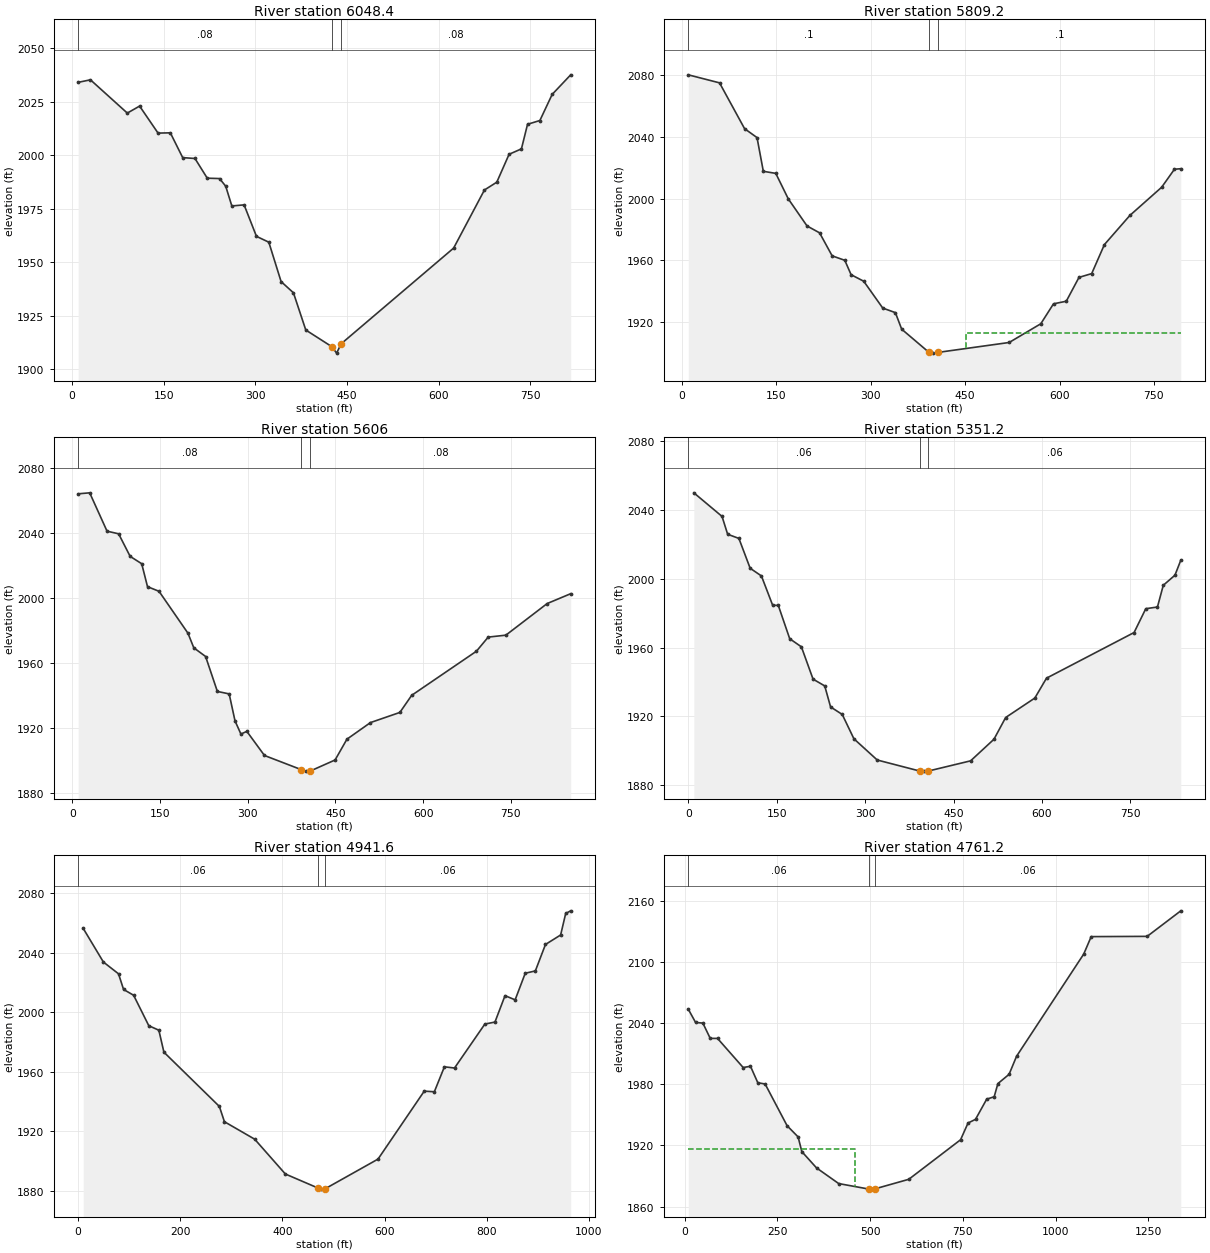
Type RM Length L Ch R = 1 ,6048.4  ,238.6,239.2,239.7
XS GIS Cut Line= 4
     1811374.479       93918.581     1811541.229       94145.546
     1811684.818       94400.302     1811754.297       94631.898
#Sta/Elev= 30
    10.1 2034.02    30.2  2035.2    90.5 2019.66   110.6 2022.93   140.8 2010.31
   160.9 2010.44   181.1 1998.86   201.2 1998.45   221.3 1989.25   241.4 1989.07
   251.5  1985.5   261.5 1976.28   281.6 1976.78   301.8 1962.08     322 1959.35
   342.1 1940.95   362.3 1935.71   382.5 1918.33   425.4 1910.49   432.9 1907.53
   440.4  1911.9   624.4  1956.6   674.8 1983.74     695 1987.38   715.1 2000.42
   735.3 2002.94   745.3 2014.43   765.5 2016.19   785.6 2028.39   815.9 2037.53
#Mann= 3 , 0 , 0
    10.1     .08       0   425.4    .045       0   440.4     .08       0
Bank Sta=425.4,440.4
XS Rating Curve= 0 ,0
Exp/Cntr=0.3,0.1

Type RM Length L Ch R = 1 ,5809.2  ,201.2,203.2,205.3
XS GIS Cut Line= 4
     1811249.417       94006.588     1811318.896       94224.288
     1811476.382         94516.1     1811638.499        94682.85
#Sta/Elev= 30
     9.9  2080.2    59.6    2075    99.4 2045.34   119.2 2039.55   129.2 2017.72
     149 2016.39   168.9 1999.86   198.7 1982.33   218.6 1977.88   238.6 1962.98
   258.7 1960.09   268.7 1950.78   288.8 1946.53     319 1929.17   339.1  1926.2
   349.1  1915.5   391.8 1900.72   399.3 1899.99   406.8 1900.46   519.9 1906.88
   570.2    1919   590.4 1931.92   610.7 1933.59   630.9 1949.04   651.1 1951.49
   671.3 1970.27   711.8 1989.16   762.3 2007.41   782.6 2019.06   792.7 2019.41
#Mann= 3 , 0 , 0
     9.9      .1       0   391.8    .045       0   406.8      .1       0
#XS Ineff= 2 , 0
                          451.67         1913.05
Permanent Ineff=
       F       F
Bank Sta=391.8,406.8
XS Rating Curve= 0 ,0
Exp/Cntr=0.3,0.1

Type RM Length L Ch R = 1 ,5606    ,254.4,254.8,255.1
XS GIS Cut Line= 4
     1811051.836        94118.82     1811152.146       94289.135
     1811322.408       94676.339     1811494.909       94831.071
#Sta/Elev= 30
     9.9    2064    29.6 2064.61    59.3 2040.99    79.1 2039.38    98.8 2025.49
   118.6 2020.94   128.5 2006.82   148.2 2003.97   197.7 1978.16   207.7 1969.16
   227.9 1963.81     248  1942.3   268.2 1940.78   278.2 1924.16   288.3 1916.05
   298.4 1917.71   328.6 1902.85   391.6 1894.13   399.1 1893.22   406.6 1893.23
   449.4 1900.09   469.6 1912.87   509.9 1923.12   560.2 1929.37   580.4  1939.9
   691.2 1967.07   711.3 1975.76   741.5 1976.95   812.1 1996.41   852.4 2002.49
#Mann= 3 , 0 , 0
     9.9     .08       0   391.6    .045       0   406.6     .08       0
Bank Sta=391.6,406.6
XS Rating Curve= 0 ,0
Exp/Cntr=0.3,0.1

Type RM Length L Ch R = 1 ,5351.2  ,404.2,409.6,413
XS GIS Cut Line= 4
     1810913.934        94164.76      1810900.67        94326.46
     1811045.612       94673.586     1810990.029       94965.397
#Sta/Elev= 30
     9.5 2049.99    57.3 2036.27    66.8  2025.9    85.9 2023.48     105 2006.13
   124.1 2001.66   143.2 1984.59   152.7 1984.55   172.1 1965.15   191.9 1960.44
   211.7 1941.65   231.5 1937.71   241.4 1925.51   261.2 1921.12     281 1906.96
   320.6 1894.62   392.3 1888.24   399.8 1888.16   407.3 1888.22     479 1894.15
   518.6 1906.71   538.4 1919.33   587.9 1930.65   607.7 1942.21   756.3 1968.76
   776.1 1982.61   795.9 1983.59   805.8 1996.22   825.6 2002.09   835.5 2010.79
#Mann= 3 , 0 , 0
       0     .06       0   392.3    .045       0   407.3     .06       0
Bank Sta=392.3,407.3
XS Rating Curve= 0 ,0
Exp/Cntr=0.3,0.1

Type RM Length L Ch R = 1 ,4941.6  ,178.7,180.4,181.9
XS GIS Cut Line= 4
     1810827.911       94154.809     1810642.634       94469.781
     1810670.426       94770.856     1810837.175       95016.349
#Sta/Elev= 30
     9.9 2056.39    49.4 2033.79      79 2025.88    88.9 2015.37   108.6 2011.46
   138.3 1991.01     158 1987.97   167.9 1973.22   276.5 1936.76   286.4 1926.49
   345.7 1914.74   405.7 1891.36   468.8 1882.05   476.3 1881.19   483.8 1881.46
   587.2 1901.37   677.7 1947.03   697.5 1946.62   717.2 1963.38     737 1962.57
   796.4  1992.1   816.2 1993.46   835.9  2011.2   855.7 2008.38   875.5 2026.27
   895.3 2027.81   915.1 2045.59   944.8 2051.97   954.7 2066.42   964.5  2068.2
#Mann= 3 , 0 , 0
       0     .06       0   468.8    .045       0   483.8     .06       0
Bank Sta=468.8,483.8
XS Rating Curve= 0 ,0
Exp/Cntr=0.3,0.1

Type RM Length L Ch R = 1 ,4761.2  ,270.8,304.6,337.3
XS GIS Cut Line= 3
     1810669.982       94146.158     1810494.764       94384.823
     1810865.318       95306.577
#Sta/Elev= 30
     9.9 2053.74    29.6 2040.69    49.3 2040.04    69.1 2025.05    88.8    2025
   157.9 1996.42   177.6 1997.68   197.4 1981.46   217.1 1980.26   276.3 1939.31
     306  1928.3     316 1913.89   355.7 1897.88   415.4 1882.51   497.4 1877.07
   504.9 1877.06   512.4 1877.26   604.3  1886.7   743.9 1925.53     764 1941.95
   784.2 1945.57   814.3 1965.37   834.5 1967.73   844.5 1980.66   874.7 1989.77
   894.8 2007.48  1075.9 2107.83    1096 2124.94  1246.9 2125.19  1337.5 2150.26
#Mann= 3 , 0 , 0
     9.9     .06       0   497.4    .045       0   512.4     .06       0
#XS Ineff= 2 , 0
          460.47 1916.45
Permanent Ineff=
       F       F
Bank Sta=497.4,512.4
XS Rating Curve= 0 ,0
Exp/Cntr=0.3,0.1

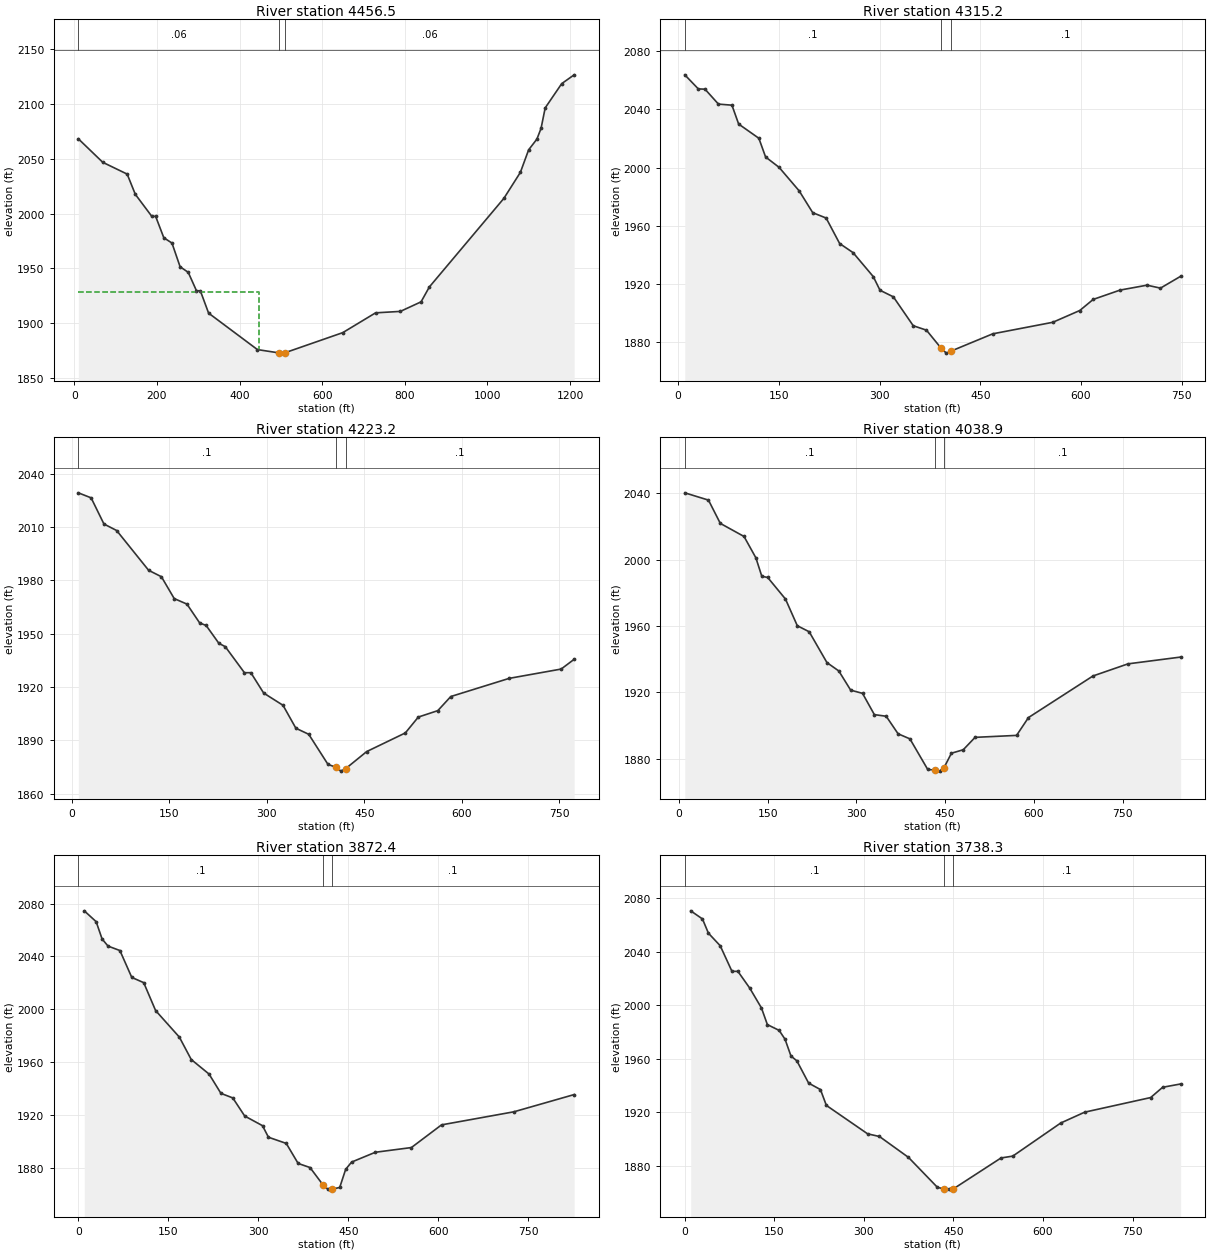
Type RM Length L Ch R = 1 ,4456.5  ,155.5,141.3,127
XS GIS Cut Line= 4
     1810581.373       94102.016     1810445.732       94450.998
     1810137.754         94516.1     1809824.435       94931.948
#Sta/Elev= 30
     9.9 2068.34      69 2046.88   128.1 2036.11   147.8 2017.66   187.2  1997.8
   197.1 1997.42   216.8 1977.99   236.5 1973.16   256.2 1951.52   275.9 1946.41
   295.6 1929.82   305.4 1929.38   325.2 1909.17   443.3  1875.9   494.8 1872.91
   502.3 1872.66   509.8 1872.98   649.9 1891.37   729.3 1909.44   789.3 1910.76
   839.4 1919.49   859.4 1933.05  1039.7 2013.91  1079.7 2037.67  1099.7 2058.25
  1119.8  2068.1  1129.8 2077.89  1139.8 2096.56  1179.8 2118.72  1209.9 2126.75
#Mann= 3 , 0 , 0
     9.9     .06       0   494.8    .045       0   509.8     .06       0
#XS Ineff= 2 , 0
           448.1 1928.26
Permanent Ineff=
       F       F
Bank Sta=494.8,509.8
XS Rating Curve= 0 ,0
Exp/Cntr=0.3,0.1

Type RM Length L Ch R = 1 ,4315.2  ,91.7,92,92.6
XS GIS Cut Line= 4
     1810559.369       94079.091     1810323.069       94280.876
     1810190.315       94426.905     1810020.391       94596.829
#Sta/Elev= 30
      10 2063.63    30.1 2053.98    40.1 2053.78    60.1 2043.54    80.2  2042.8
    90.2 2029.85   120.3 2020.09   130.3 2007.26   150.4 2000.15   180.4 1983.95
   200.5 1969.03   220.5 1965.34   240.6 1947.86   260.6  1941.6   290.7 1925.14
   300.7 1915.79   320.6 1911.27   350.2 1891.44   369.9 1888.39     392 1875.87
   399.5 1872.64     407 1874.13   468.6 1885.89   558.1 1893.81   598.2 1901.89
   618.2  1909.5   658.3 1915.91   698.3 1919.27   718.4 1917.25   748.4 1925.36
#Mann= 3 , 0 , 0
      10      .1       0     392    .045       0     407      .1       0
Bank Sta=392,407
XS Rating Curve= 0 ,0
Exp/Cntr=0.3,0.1

Type RM Length L Ch R = 1 ,4223.2  ,185.5,184.3,183.1
XS GIS Cut Line= 4
     1810493.039       94001.545     1810281.549       94192.893
     1810125.449       94359.063     1809974.385       94570.553
#Sta/Elev= 30
     9.8 2029.34    29.5 2026.51    49.2  2011.8    68.8 2008.11     118 1985.72
   137.7 1982.09   157.4 1969.79     177 1966.68   196.7 1956.02   206.5 1954.67
   226.2 1944.58     236 1942.72   265.5 1928.05   275.4 1928.05   295.1 1916.59
   324.9 1909.69   344.7 1896.78   364.5 1893.36   394.2 1876.37   406.6 1874.81
   414.1 1872.62   421.6 1874.09   453.7 1883.63   513.2 1894.13   533.2 1903.07
   563.2 1906.68   583.2 1914.63   673.1 1924.86   753.1  1930.1   773.1  1935.6
#Mann= 3 , 0 , 0
     9.8      .1       0   406.6    .045       0   421.6      .1       0
Bank Sta=406.6,421.6
XS Rating Curve= 0 ,0
Exp/Cntr=0.3,0.1

Type RM Length L Ch R = 1 ,4038.9  ,167.5,166.5,165.5
XS GIS Cut Line= 4
     1810383.246       93858.366      1810225.76         93964.9
     1809947.845       94293.767     1809766.983       94431.106
#Sta/Elev= 30
      10 2040.25      50 2035.86      70 2021.84   110.1 2013.95   130.1  2001.1
   140.1    1990   150.1 1989.24   180.1 1976.26   200.1 1960.18   220.2 1956.54
   250.2 1937.96   270.2 1932.94   290.3 1921.36   310.3 1919.44   330.3 1906.62
   350.3 1905.64   370.4 1895.07   390.4 1892.02   420.4 1873.64     433 1873.11
   440.5 1872.58     448 1874.64   460.5 1883.37   480.5 1885.46   500.5 1892.93
   570.6 1894.11   590.7 1904.85   699.7 1929.91   758.9 1937.21   847.8  1941.3
#Mann= 3 , 0 , 0
      10      .1       0     433    .045       0     448      .1       0
Bank Sta=433,448
XS Rating Curve= 0 ,0
Exp/Cntr=0.3,0.1

Type RM Length L Ch R = 1 ,3872.4  ,134.7,134,133.4
XS GIS Cut Line= 4
     1810222.176       93736.588     1810020.391       93941.028
     1809887.638       94113.607     1809648.682       94328.667
#Sta/Elev= 30
     9.9 2074.47    29.7 2066.26    39.6 2053.16    49.5 2047.77    69.3  2044.4
    89.1 2024.05     109 2020.07   128.8 1998.96   168.4 1978.85   188.2 1961.89
   217.9 1950.87   237.7 1936.26   257.5 1932.79   277.3 1919.11     307 1911.78
   316.9 1903.04   346.6 1898.36   366.4 1883.19   386.2 1880.09   408.4 1866.61
   415.9 1863.74   423.4 1863.76   435.7    1865   445.6  1878.7   455.5 1884.22
   495.1 1891.65   555.2 1895.22   605.4 1912.39     726 1922.29   826.5 1935.34
#Mann= 3 , 0 , 0
       0      .1       0   408.4    .045       0   423.4      .1       0
Bank Sta=408.4,423.4
XS Rating Curve= 0 ,0
Exp/Cntr=0.3,0.1

Type RM Length L Ch R = 1 ,3738.3  ,118.8,120.9,123
XS GIS Cut Line= 4
     1810169.075       93691.452     1809892.948       93882.616
      1809773.47        94047.23      1809574.34       94259.636
#Sta/Elev= 30
     9.9  2070.6    29.6 2064.52    39.5 2053.92    59.3 2044.48      79 2025.34
    88.9 2025.34   108.7 2012.85   128.4 1997.93   138.3  1985.5     158 1981.17
   167.9 1974.55   177.8 1962.01   187.7 1958.38   207.4 1941.73   227.2  1936.9
   237.1 1925.06   306.2 1903.79     326 1901.81   374.6 1886.19     423 1863.82
   434.9 1862.47   442.4 1862.44   449.9 1862.66   529.6 1885.75   549.3 1887.13
   629.6 1911.89   669.8 1920.01   780.2 1930.93   800.3 1938.62   830.4  1941.1
#Mann= 3 , 0 , 0
       0      .1       0   434.9    .045       0   449.9      .1       0
Bank Sta=434.9,449.9
XS Rating Curve= 0 ,0
Exp/Cntr=0.3,0.1

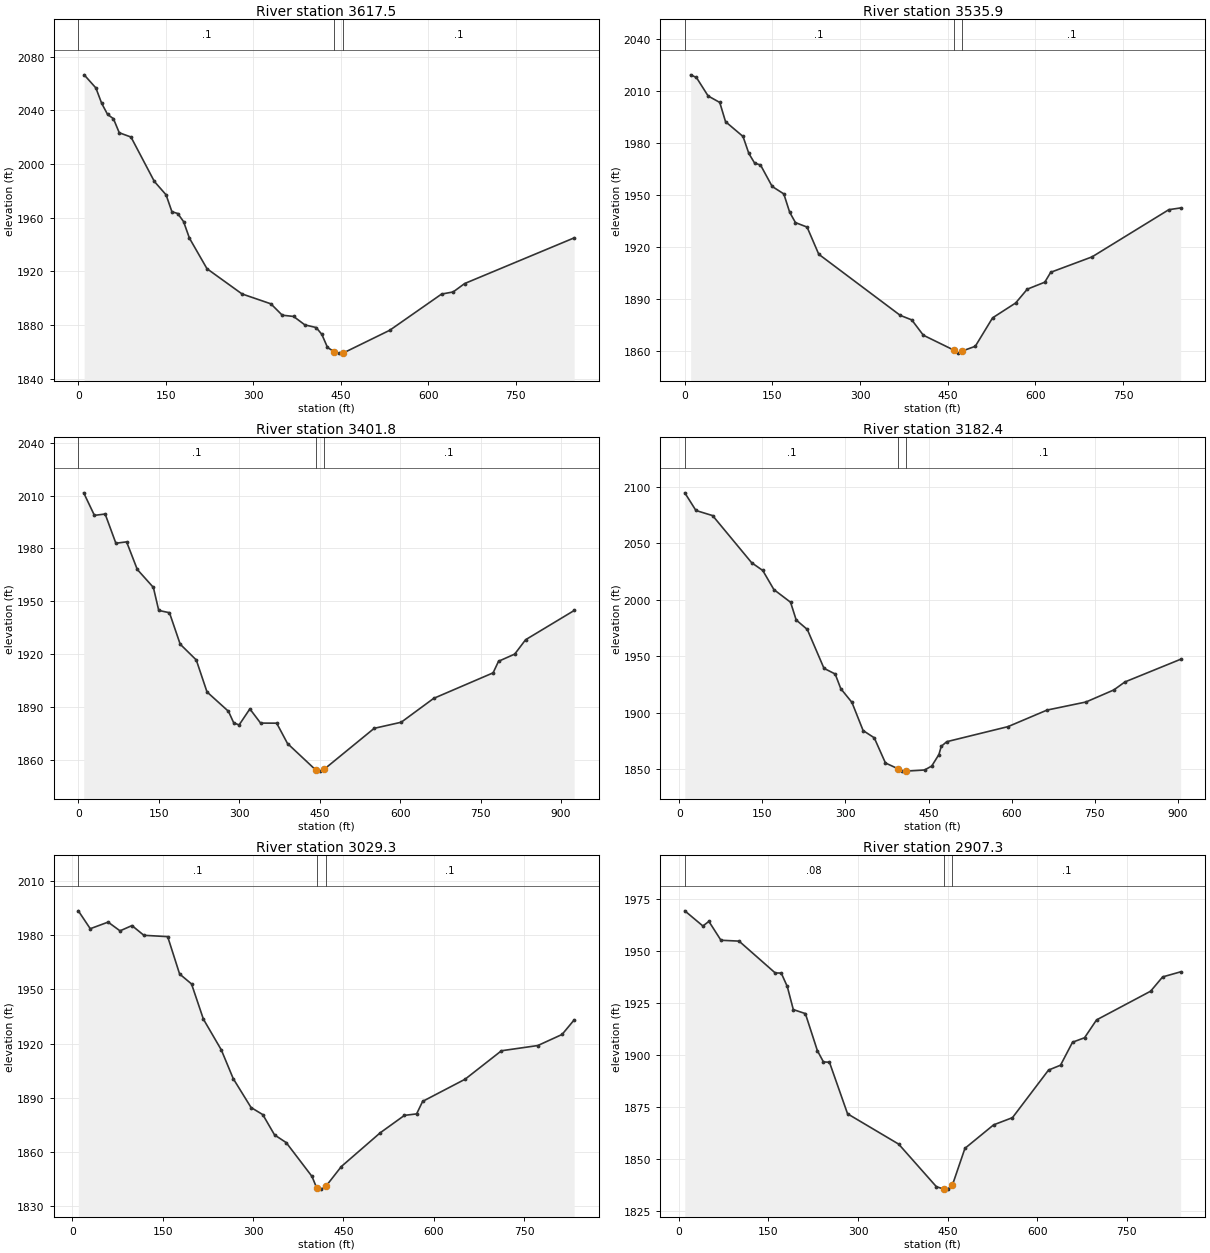
Type RM Length L Ch R = 1 ,3617.5  ,78.6,81.5,84.4
XS GIS Cut Line= 4
     1810115.735       93641.904     1809836.269       93778.214
     1809689.048       93946.014     1809462.229       94166.476
#Sta/Elev= 30
      10 2066.58    30.1 2056.79    40.1 2045.26    50.2 2037.03    60.2 2033.85
    70.2 2023.37    90.3 2020.18   130.4 1987.05   150.5 1977.07   160.5 1964.48
   170.5 1963.13   180.5 1957.11   190.6 1944.73   220.7 1921.94   280.8 1903.13
   330.3 1895.75   349.8 1887.27   369.2 1886.35   388.6 1880.04     408 1878.07
   417.7 1872.97   427.4 1863.22   439.3  1859.9   446.8 1858.98   454.3 1859.05
   534.2 1876.05   623.1 1903.04   642.9 1904.61   662.7  1910.9   850.5 1944.95
#Mann= 3 , 0 , 0
       0      .1       0   439.3    .045       0   454.3      .1       0
Bank Sta=439.3,454.3
XS Rating Curve= 0 ,0
Exp/Cntr=0.3,0.1

Type RM Length L Ch R = 1 ,3535.9  ,111.3,134.1,156.9
XS GIS Cut Line= 4
     1810025.701       93508.252     1809765.505       93755.173
     1809587.616       93911.822     1809446.897       94121.572
#Sta/Elev= 30
      10 2019.47    19.9 2017.93    39.9 2007.27    59.8 2003.54    69.7 1992.43
    99.6  1983.9   109.6 1974.07   119.6 1968.46   129.5 1967.47   149.5 1955.05
   169.4 1950.76   179.4  1940.2   189.3  1934.2   209.2 1931.61   229.2 1915.93
   368.6 1880.66   388.3 1878.05   408.1 1869.21   459.8 1860.69   467.3 1858.87
   474.8  1860.1     497 1862.82   526.6 1879.23   566.1 1887.82   585.9 1895.77
   615.9 1899.81     626 1905.51   696.8 1914.42   828.1 1941.65   848.3 1942.66
#Mann= 3 , 0 , 0
       0      .1       0   459.8    .045       0   474.8      .1       0
Bank Sta=459.8,474.8
XS Rating Curve= 0 ,0
Exp/Cntr=0.3,0.1

Type RM Length L Ch R = 1 ,3401.8  ,254.8,219.4,184
XS GIS Cut Line= 4
     1809940.739       93404.705     1809744.265       93718.002
      1809558.41       93670.211     1809314.144       93938.373
#Sta/Elev= 30
      10 2011.58      30 1998.79      50 1999.56      70 1982.98      90 1983.76
   109.9 1968.11   139.9 1957.92   149.9 1944.86   169.9 1943.56   189.9 1925.71
   219.9 1916.75   239.9 1898.61   279.9 1887.62   289.8 1881.02   299.8 1879.92
   319.8 1888.99   339.8 1880.94   369.8  1880.9     390 1869.35   443.1 1854.21
   450.6 1853.69   458.1  1854.7   551.6 1877.97     602 1881.43   662.5 1894.97
   773.3 1909.45   783.4 1916.01   813.6 1920.09   833.8 1928.22   924.4 1944.82
#Mann= 3 , 0 , 0
       0      .1       0   443.1    .045       0   458.1      .1       0
Bank Sta=443.1,458.1
XS Rating Curve= 0 ,0
Exp/Cntr=0.3,0.1

Type RM Length L Ch R = 1 ,3182.4  ,156.3,153.1,150
XS GIS Cut Line= 4
     1809796.854       93189.816     1809640.717       93399.394
     1809576.995       93590.559      1809273.04       93911.455
#Sta/Elev= 30
    10.1 2094.58    30.2 2078.94    60.3 2074.42   130.7 2032.71   150.8 2025.81
   170.9 2008.88     201 1997.67   211.1 1981.98   231.2 1973.58   261.3 1939.15
   281.5 1934.13   291.6 1921.14   311.7 1909.02   331.9 1884.06     352 1877.63
   372.2 1855.34   394.9 1850.21   402.4 1848.12   409.9 1848.13  442.85 1849.12
  455.73 1852.64  468.73 1862.84   472.9 1870.08   482.9  1874.2   593.4 1887.53
   663.8 1902.18   734.1 1909.34   784.3 1920.01   804.4 1927.11   904.9 1947.18
#Mann= 3 , 0 , 0
    10.1      .1       0   394.9    .045       0   409.9      .1       0
Bank Sta=394.9,409.9
XS Rating Curve= 0 ,0
Exp/Cntr=0.3,0.1

Type RM Length L Ch R = 1 ,3029.3  ,124.6,122,119.3
XS GIS Cut Line= 4
     1809635.407       93115.303      1809475.34       93365.045
      1809438.93       93566.089     1809247.767        93837.48
#Sta/Elev= 30
     9.9 1993.59    29.7 1983.67    59.3 1987.34    79.1 1982.49    98.9 1985.41
   118.7 1980.02   158.2 1979.28     178 1958.58   197.8 1953.05   217.5 1933.53
   247.2 1916.51     267 1900.57   296.6 1884.55   316.1  1880.6   335.6 1869.36
     355 1865.08  397.76 1846.33   405.9 1839.68   413.4  1839.3   420.9 1840.91
  446.43 1851.82     511 1870.53   551.2 1880.19   571.4 1881.01   581.4 1887.95
   651.8 1900.22   712.2 1916.01   772.6 1918.91   812.8 1925.04   832.9 1933.11
#Mann= 3 , 0 , 0
     9.9      .1       0   405.9    .045       0   420.9      .1       0
Bank Sta=405.9,420.9
XS Rating Curve= 0 ,0
Exp/Cntr=0.3,0.1

Type RM Length L Ch R = 1 ,2907.3  ,87.1,86.1,85
XS GIS Cut Line= 4
     1809584.487       93087.978     1809343.074       93359.323
     1809332.729       93524.183     1809178.736       93794.999
#Sta/Elev= 30
    10.1 1969.46    40.4 1962.16    50.4 1964.37    70.6  1955.3   100.9 1954.88
   161.4 1939.57   171.5  1939.5   181.6 1933.04   191.7 1921.93   211.9 1919.99
     232 1902.15   242.1 1896.75   252.2 1896.58   282.5 1871.76  368.06 1857.17
   431.2 1836.66   443.1  1835.6   450.6 1835.51   458.1 1837.58  478.93 1855.14
  526.96 1866.45   558.5 1869.92   618.8 1892.81   638.9 1895.16     659 1906.22
   679.1 1908.37   699.2 1916.96   789.7 1930.78   809.8 1937.65   839.9  1940.1
#Mann= 3 , 0 , 0
    10.1     .08       0   443.1    .045       0   458.1      .1       0
Bank Sta=443.1,458.1
XS Rating Curve= 0 ,0
Exp/Cntr=0.3,0.1