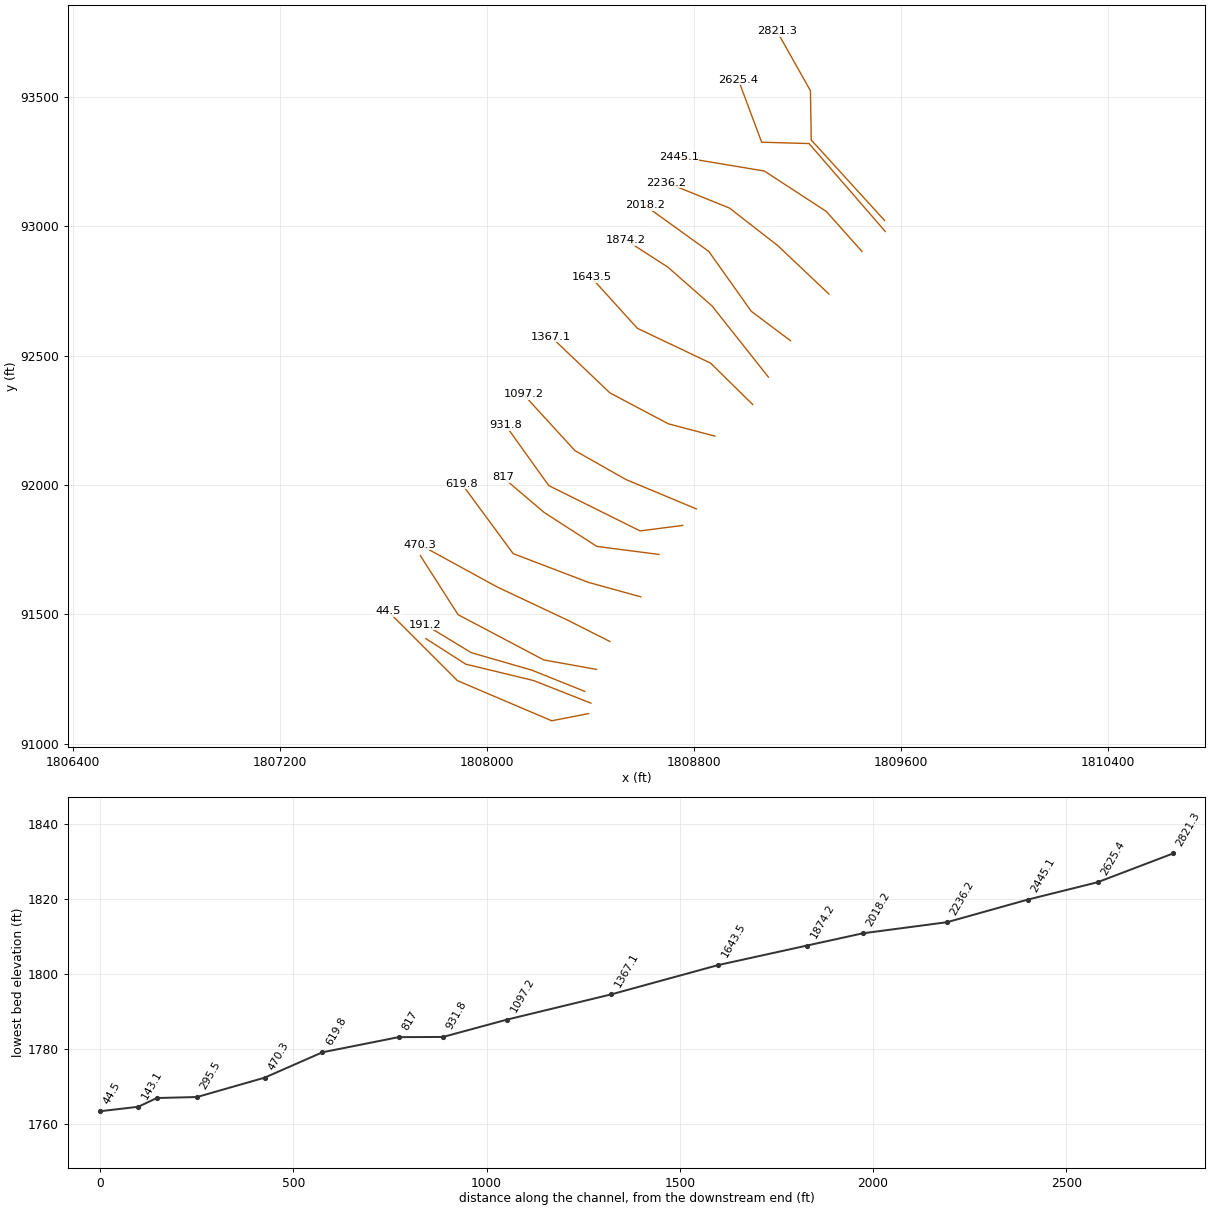
HEC-RAS study North Fork Big Creek.prj: NFk Big Ck

--- North Fork Big Creek.g01 (geometry) --- (continued)

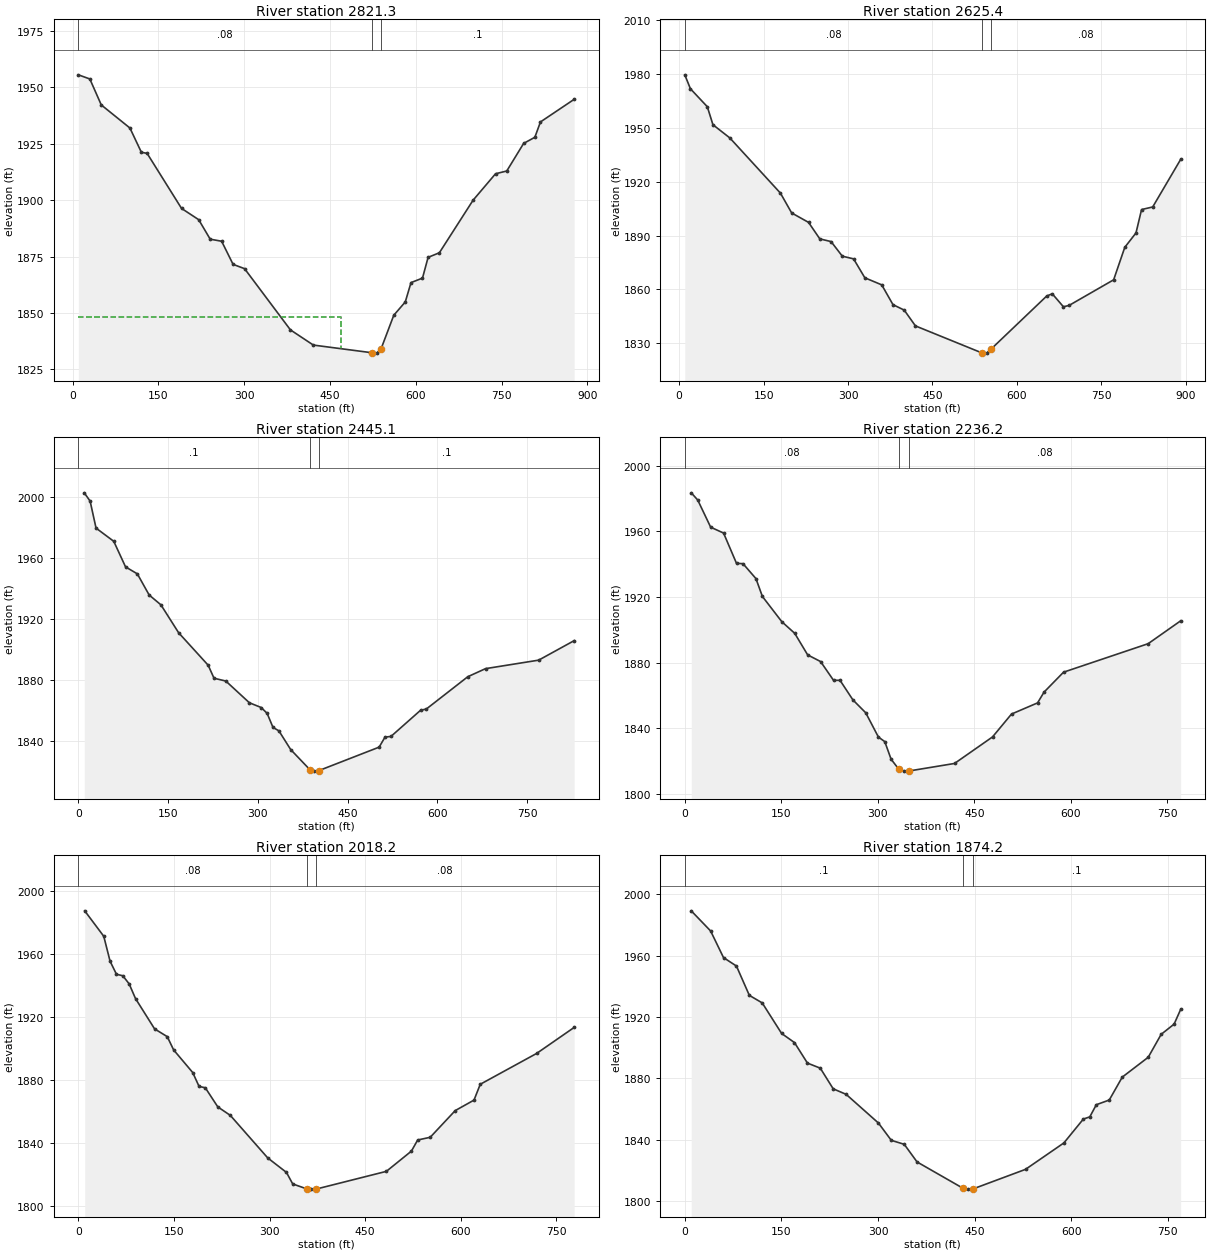
Type RM Length L Ch R = 1 ,2821.3  ,160.3,195.9,231.5
XS GIS Cut Line= 4
     1809537.169       93022.375     1809253.716       93333.385
     1809250.422       93524.183     1809120.324       93755.173
#Sta/Elev= 30
      10 1955.56    30.1 1953.73    50.1 1942.22   100.2 1931.98   120.2 1921.23
   130.2 1920.76   190.4 1896.36   220.4 1891.36   240.5 1882.72   260.5 1881.81
   280.5 1871.56   300.6 1869.65   380.7 1842.53   420.8 1835.79   523.8 1832.37
   531.3 1832.22   538.8 1833.86   561.4 1849.01   581.5  1854.9   591.5 1863.47
   611.6 1865.47   621.4 1874.67   641.1  1876.7     700 1899.99   739.3 1911.72
   758.9 1912.94   788.4 1925.17     808 1927.88   817.8 1934.68   876.7  1944.7
#Mann= 3 , 0 , 0
      10     .08       0   523.8    .045       0   538.8      .1       0
#XS Ineff= 2 , 0
          469.32 1848.43
Permanent Ineff=
       F       F
Bank Sta=523.8,538.8
XS Rating Curve= 0 ,0
Exp/Cntr=0.3,0.1

Type RM Length L Ch R = 1 ,2625.4  ,193.8,180.3,166.6
XS GIS Cut Line= 4
     1809539.825       92979.894     1809245.112       93319.743
     1809061.913       93325.053     1808971.641       93566.664
#Sta/Elev= 30
      10 1979.56      20 1971.79      50 1961.79      60 1951.76      90 1944.41
   179.9 1913.66   199.9 1902.61   229.9 1897.35   249.9 1888.16   269.9 1886.66
   289.9 1878.52   309.9 1877.03   329.9 1866.48   359.9 1862.55   379.9 1851.52
   399.9 1848.47   419.8 1839.68   538.8 1824.52   546.3 1824.51   553.8 1826.64
     653 1856.31   662.9 1857.58   682.7 1850.35   692.6 1851.05     772 1865.36
   791.8 1883.47   811.7 1891.47   821.6  1904.5   841.4 1905.94     891 1932.41
#Mann= 3 , 0 , 0
      10     .08       0   538.8    .045       0   553.8     .08       0
Bank Sta=538.8,553.8
XS Rating Curve= 0 ,0
Exp/Cntr=0.3,0.1

Type RM Length L Ch R = 1 ,2445.1  ,210.7,208.9,207.1
XS GIS Cut Line= 4
     1809449.552       92902.897     1809311.718        93057.39
     1809072.533        93213.54     1808741.414       93268.781
#Sta/Elev= 30
     9.9 2002.97    19.7 1997.51    29.6 1979.76    59.2 1971.07    78.9 1954.24
    98.6 1949.66   118.3 1935.77     138 1929.27   167.6  1910.9   216.9 1889.57
   226.7 1880.99   246.4 1879.15   285.8 1864.85   305.5 1861.73   315.4 1857.91
   325.2 1848.67   335.1 1846.37   354.8 1834.07   386.7 1820.91   394.2 1819.88
   401.7  1820.2   502.6 1835.67   512.4 1842.29   522.3 1842.69   571.7 1859.89
   581.5 1860.76   650.7 1881.99   680.3  1887.3   769.1 1892.89   828.4 1905.72
#Mann= 3 , 0 , 0
       0      .1       0   386.7    .045       0   401.7      .1       0
Bank Sta=386.7,401.7
XS Rating Curve= 0 ,0
Exp/Cntr=0.3,0.1

Type RM Length L Ch R = 1 ,2236.2  ,224.6,218,212.3
XS GIS Cut Line= 4
     1809321.425       92738.408     1809124.369       92925.092
     1808937.685       93070.291     1808693.958       93168.819
#Sta/Elev= 30
    10.1 1983.55    20.1 1979.16    40.2 1962.61    60.3    1959    80.4 1940.53
    90.5 1940.35   110.6 1931.25   120.6 1920.38   150.8 1904.97   170.9 1897.87
     191 1884.72   211.1 1880.66   231.2 1869.22   241.3 1869.22   261.4 1857.25
   281.3 1849.41     301 1834.61   310.9 1831.83   320.7 1821.11   332.9 1814.91
   340.4 1813.84   347.9 1813.89   419.3 1818.51   478.4  1834.7   507.9 1848.64
   548.4 1855.45   558.5 1862.03   588.8 1874.18   720.3 1891.55   770.8 1905.48
#Mann= 3 , 0 , 0
       0     .08       0   332.9    .045       0   347.9     .08       0
Bank Sta=332.9,347.9
XS Rating Curve= 0 ,0
Exp/Cntr=0.3,0.1

Type RM Length L Ch R = 1 ,2018.2  ,138.3,144,148.7
XS GIS Cut Line= 4
     1809173.426       92557.739     1809021.805       92671.217
     1808857.473       92902.897     1808610.552       93080.787
#Sta/Elev= 30
      10  1987.7    39.9 1971.52    49.8 1955.68    59.8  1947.4    69.8 1946.44
    79.7  1941.3    89.7 1931.95   119.6  1912.7   139.5 1907.75   149.5 1899.33
   179.4 1884.97   189.4 1876.13   199.2 1875.27   218.8 1863.11   238.4 1857.74
   297.1  1830.7   326.5 1821.49   336.3 1814.17   358.2 1811.04   365.7 1810.87
   373.2 1810.92   483.2 1822.16   522.5 1835.02   532.3 1842.08     552 1843.81
   591.2 1860.76   620.7 1867.44   630.5 1877.49   718.9 1897.08   777.8 1913.61
#Mann= 3 , 0 , 0
       0     .08       0   358.2    .045       0   373.2     .08       0
Bank Sta=358.2,373.2
XS Rating Curve= 0 ,0
Exp/Cntr=0.3,0.1

Type RM Length L Ch R = 1 ,1874.2  ,224.5,230.8,237
XS GIS Cut Line= 4
     1809088.069       92416.896     1808870.271       92691.737
     1808699.144       92842.121     1808538.388       92945.835
#Sta/Elev= 30
      10 1989.33    40.1 1976.17    60.1 1958.79    80.2 1953.27   100.2 1934.14
   120.2 1929.21   150.3 1909.27   170.3 1903.29   190.4 1889.91   210.4 1886.58
   230.4 1873.11   250.5  1869.5   300.6 1850.78   320.6 1839.47   340.7 1836.88
   360.6 1825.36   432.3 1808.09   439.8 1807.61   447.3 1807.72     529 1820.52
   588.6 1837.79   618.8 1853.37   628.8 1854.79   638.9 1862.73     659 1865.79
   679.2 1880.75   719.5 1893.71   739.6 1908.69   759.7 1915.36   769.8 1924.92
#Mann= 3 , 0 , 0
       0      .1       0   432.3    .045       0   447.3      .1       0
Bank Sta=432.3,447.3
XS Rating Curve= 0 ,0
Exp/Cntr=0.3,0.1

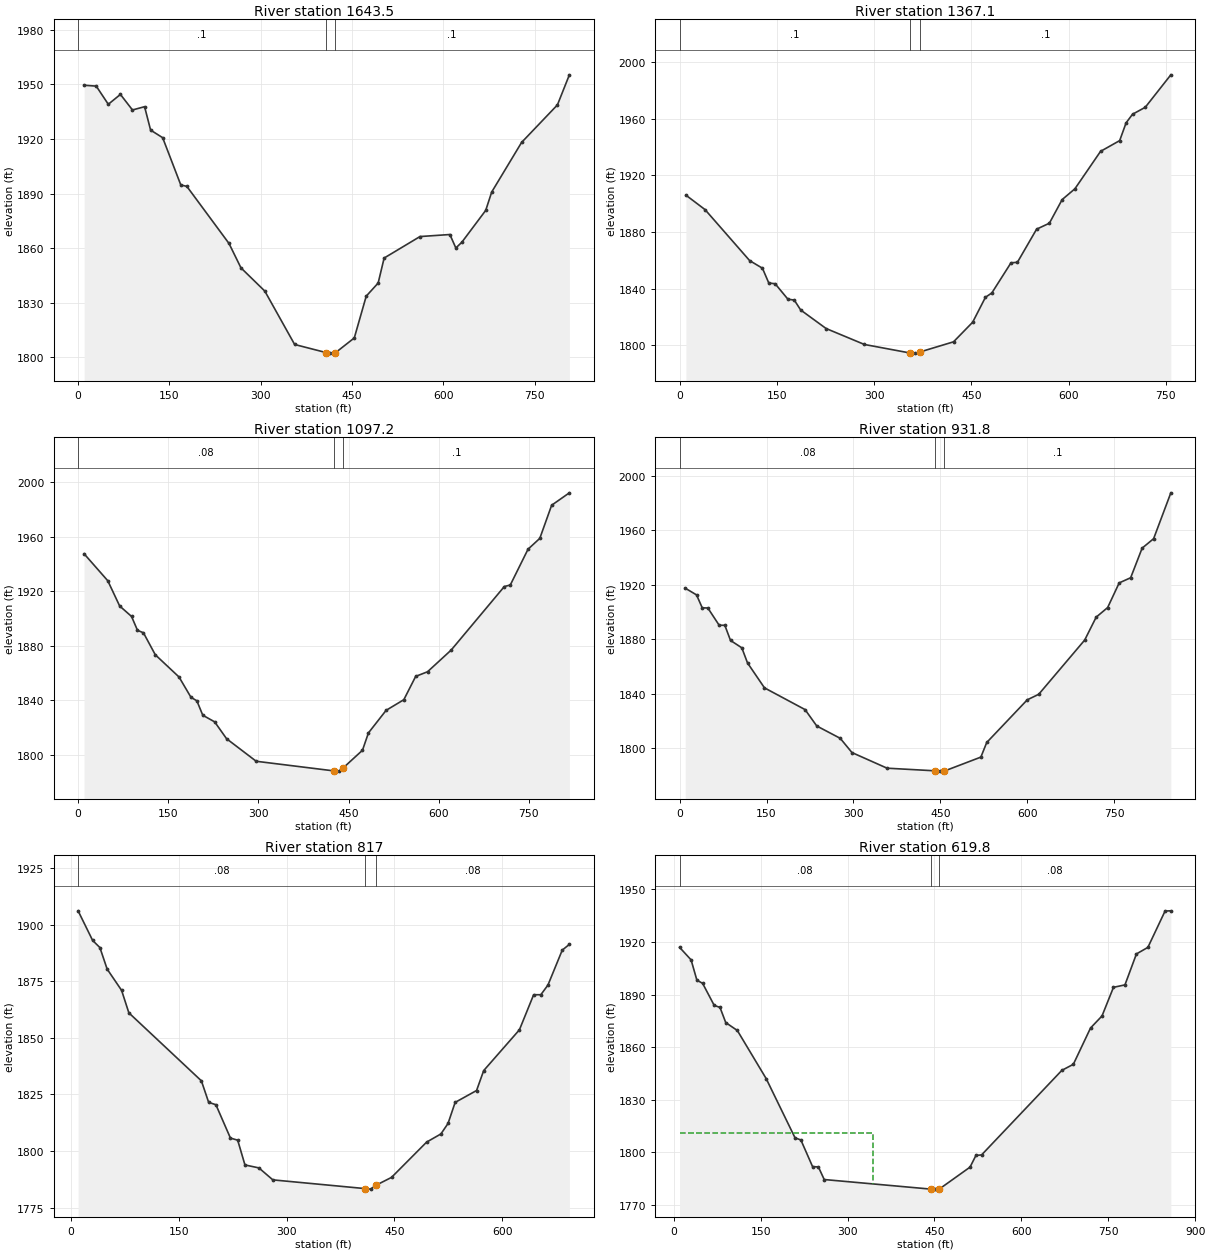
Type RM Length L Ch R = 1 ,1643.5  ,277.3,276.3,275.4
XS GIS Cut Line= 4
     1809027.397       92310.818     1808864.674       92470.897
     1808581.346        92605.53     1808403.457       92802.005
#Sta/Elev= 30
     9.9 1949.55    29.8 1949.08    49.6 1939.09    69.5 1944.52    89.3 1935.97
   109.2 1937.77   119.1 1924.91   138.9 1920.74   168.7 1894.77   178.6    1894
   247.9 1862.61   267.5 1849.23   306.7 1836.46   355.7 1807.12     407  1802.7
   414.5 1802.37     422 1802.39   453.7 1810.72   473.3 1833.68   492.9 1840.89
   502.7 1854.61   561.6 1866.42   610.7 1867.54   620.5 1860.15   630.3 1863.27
   669.6 1880.81   679.4 1890.88   728.5 1918.13   787.4 1938.77     807 1955.28
#Mann= 3 , 0 , 0
       0      .1       0     407    .045       0     422      .1       0
Bank Sta=407,422
XS Rating Curve= 0 ,0
Exp/Cntr=0.3,0.1

Type RM Length L Ch R = 1 ,1367.1  ,270.6,270,269.3
XS GIS Cut Line= 4
     1808881.368       92188.685     1808700.824       92236.476
     1808475.143       92355.954     1808246.808       92573.669
#Sta/Elev= 30
     9.8 1905.95    39.3 1895.75   108.1 1859.78   127.8 1854.43   137.6    1844
   147.4 1843.48   167.1 1832.58   176.9 1831.96   186.8 1824.96     226  1811.9
     285 1800.66     356  1794.6   363.5 1794.55     371 1795.41   422.5 1802.52
     452 1816.35   471.7 1833.92   481.6 1837.01   511.1 1858.24     521 1858.59
   550.6 1881.96   570.3 1886.16     590 1902.82   609.7 1910.45   649.2 1936.82
   678.7 1944.41   688.6 1956.94   698.5 1962.99   718.2 1967.92   757.6  1990.8
#Mann= 3 , 0 , 0
       0      .1       0     356    .045       0     371      .1       0
Bank Sta=356,371
XS Rating Curve= 0 ,0
Exp/Cntr=0.3,0.1

Type RM Length L Ch R = 1 ,1097.2  ,164.2,165.4,166.6
XS GIS Cut Line= 4
     1808809.682       91907.248      1808536.21       92021.416
     1808339.735       92132.929     1808140.605       92350.644
#Sta/Elev= 30
     9.9 1947.39    49.4 1927.55    69.1 1909.06    88.9 1901.36    98.8 1891.16
   108.7 1889.36   128.4 1873.23   167.9  1856.9   187.7 1842.05   197.6  1839.4
   207.4 1828.84   227.2 1823.96     247 1811.59   296.3 1795.04   426.4 1787.92
   433.9  1787.8   441.4 1790.33   473.1 1803.13     483 1815.85   512.4 1832.42
   541.9 1840.24   561.6 1857.35   581.3 1860.74   620.6 1876.65   709.1 1923.33
     719 1924.43   748.5 1950.71   768.1 1958.68   787.8    1983   817.3 1992.11
#Mann= 3 , 0 , 0
       0     .08       0   426.4    .045       0   441.4      .1       0
Bank Sta=426.4,441.4
XS Rating Curve= 0 ,0
Exp/Cntr=0.3,0.1

Type RM Length L Ch R = 1 ,931.8   ,116.3,114.8,113.2
XS GIS Cut Line= 4
      1808756.58       91843.526     1808591.966       91822.286
     1808238.843        91997.52     1808071.574       92231.166
#Sta/Elev= 30
     9.8 1917.48    29.3 1912.55    39.1 1903.07    48.8 1902.93    68.3 1890.28
    78.1 1890.24    87.9 1879.12   107.4  1873.7   117.2 1862.63   146.5  1844.3
   216.5 1828.35   236.7 1816.31   277.2 1807.25   297.4  1796.8     358 1785.33
   441.5 1783.38     449 1783.17   456.5 1783.18   519.8 1793.47   529.9 1804.19
   599.8 1835.51   619.6 1839.58   698.9  1879.4   718.7 1896.21   738.5 1903.25
   758.4 1921.36   778.2 1925.15     798 1946.89   817.8 1953.82   847.5 1987.49
#Mann= 3 , 0 , 0
       0     .08       0   441.5    .045       0   456.5      .1       0
Bank Sta=441.5,456.5
XS Rating Curve= 0 ,0
Exp/Cntr=0.3,0.1

Type RM Length L Ch R = 1 ,817     ,193.4,197.2,200.9
XS GIS Cut Line= 4
     1808664.832       91731.366      1808424.66       91762.355
     1808220.602       91893.944     1808061.701       92028.974
#Sta/Elev= 30
    10.1 1906.11    30.3 1893.03    40.4 1889.88    50.5 1880.36    70.6 1870.96
    80.7 1861.03   181.6 1830.98   191.7 1821.47   201.8 1820.42     222 1805.68
   232.1 1804.75   242.2 1793.81   261.6  1792.5     281 1787.21   409.5 1783.35
     417 1783.12   424.5 1784.83   446.1 1788.31   494.9  1803.9   514.8 1807.51
   524.7 1812.14   534.6 1821.45   564.4  1826.7   574.3  1835.5     624 1853.53
   643.8 1869.03   653.8 1869.03   663.7 1873.31   683.6 1888.75   693.5 1891.29
#Mann= 3 , 0 , 0
    10.1     .08       0   409.5    .045       0   424.5     .08       0
Bank Sta=409.5,424.5
XS Rating Curve= 0 ,0
Exp/Cntr=0.3,0.1

Type RM Length L Ch R = 1 ,619.8   ,151.3,149.6,147.9
XS GIS Cut Line= 4
     1808594.621         91567.4     1808392.836       91623.156
     1808101.276       91734.532     1807901.649       92005.485
#Sta/Elev= 30
      10 1916.98    29.9 1909.82    39.9 1898.26    49.8 1896.44    69.8 1883.86
    79.8 1882.71    89.7 1874.07   109.7 1869.55   159.5 1842.11   209.3 1808.34
   219.4 1807.11   239.6  1791.9   249.6 1791.75   259.7 1784.54   443.5 1779.08
     451 1779.07   458.5 1779.15   511.4 1791.62   521.5 1798.25   531.4 1798.61
   669.9 1846.82   689.7 1850.26   719.4 1870.97   739.2 1877.84     759 1894.17
   778.8 1895.56   798.6 1913.21   818.4 1916.96   848.1 1937.71     858  1937.8
#Mann= 3 , 0 , 0
      10     .08       0   443.5    .045       0   458.5     .08       0
#XS Ineff= 2 , 0
          343.67 1811.03
Permanent Ineff=
       F       F
Bank Sta=443.5,458.5
XS Rating Curve= 0 ,0
Exp/Cntr=0.3,0.1

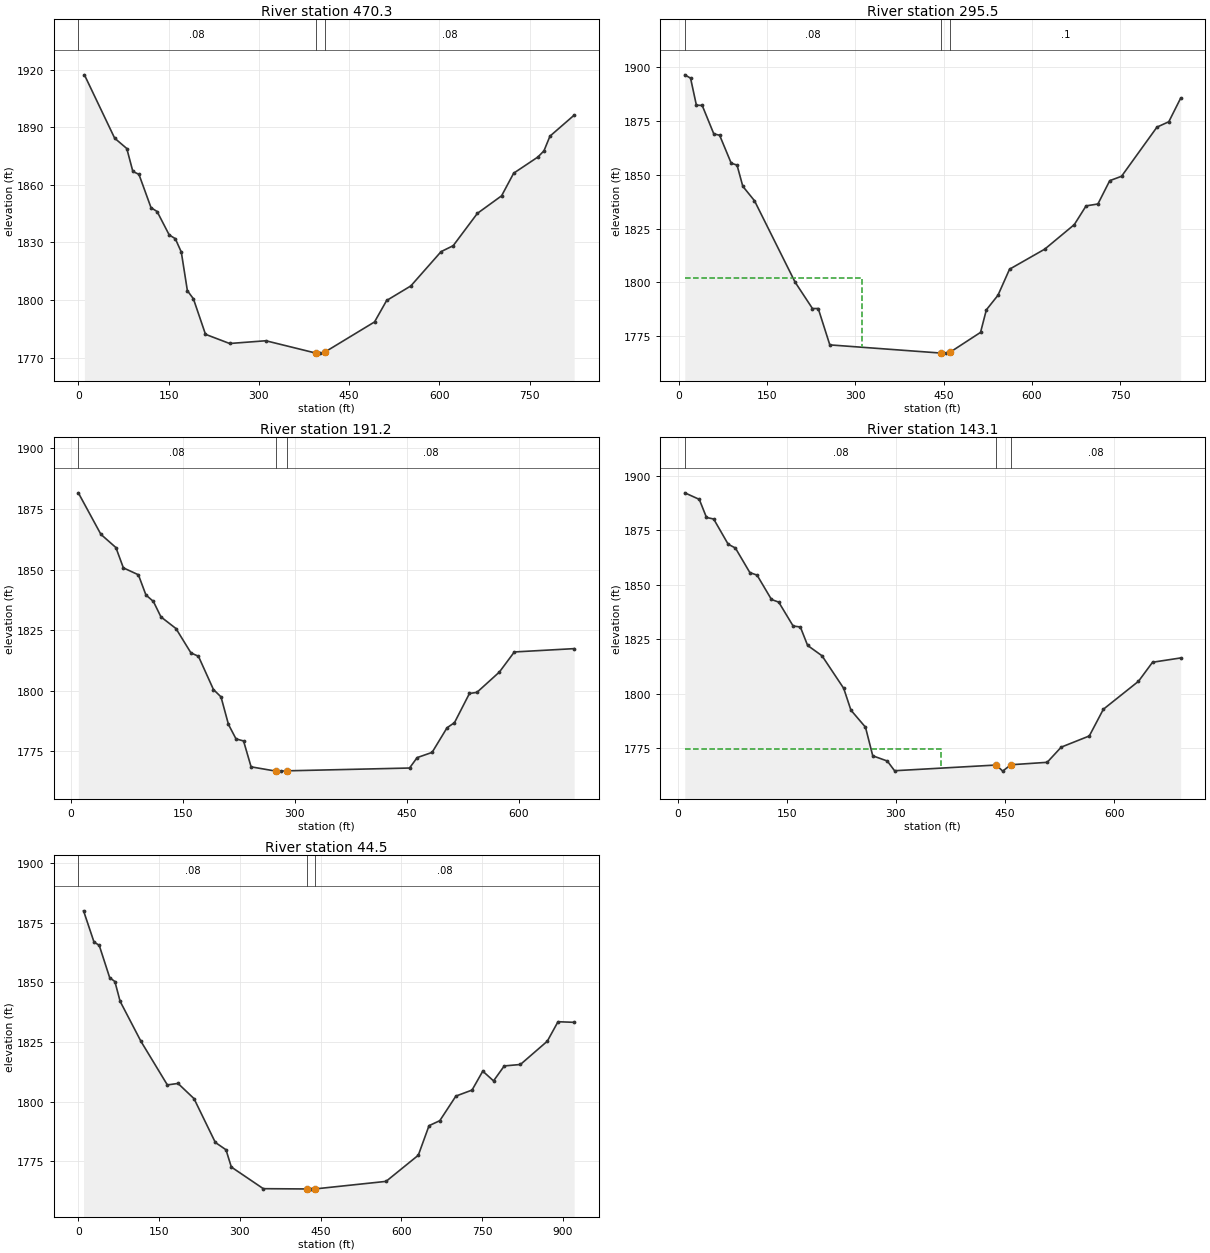
Type RM Length L Ch R = 1 ,470.3   ,175.9,174.8,173.7
XS GIS Cut Line= 4
     1808475.143        91394.82     1808313.401         91476.5
     1808041.121       91604.724     1807741.222       91768.621
#Sta/Elev= 30
    10.1 1917.38    60.4 1884.33    80.5 1878.97    90.6 1867.01   100.7 1865.49
   120.8 1848.12   130.9 1846.11     151 1833.92   161.1 1831.96   171.1    1825
   181.2 1804.84   191.2 1800.63   211.3  1782.1   251.4 1777.31   311.6 1778.74
   394.4 1772.33   401.9 1772.29   409.4  1772.8   492.2 1788.55   512.3 1799.73
   552.5 1807.32   602.8 1825.21   622.9  1828.3   663.1 1845.16   703.3  1854.3
   723.4  1866.1   763.6 1874.52   773.7 1877.74   783.7 1885.41   823.9 1896.36
#Mann= 3 , 0 , 0
       0     .08       0   394.4    .045       0   409.4     .08       0
Bank Sta=394.4,409.4
XS Rating Curve= 0 ,0
Exp/Cntr=0.3,0.1

Type RM Length L Ch R = 1 ,295.5   ,99.6,104.3,108.9
XS GIS Cut Line= 4
     1808423.421       91286.853     1808219.528        91323.58
     1807888.374       91498.368     1807742.346       91726.703
#Sta/Elev= 30
     9.9 1896.46    19.7 1894.91    29.6 1882.36    39.5 1882.23    59.2 1869.02
    69.1 1868.38    88.8 1855.39    98.7 1854.51   108.5 1844.65   128.3 1837.97
   197.3 1800.15   226.9 1787.85   236.7 1787.85   256.4 1770.95     446 1767.13
   453.5 1767.12     461 1767.58   512.6 1776.76   522.5 1787.24   542.2    1794
   561.9 1806.12   621.8 1815.46     672 1826.86     692 1835.55   712.1 1836.43
   732.2 1847.27   752.3 1849.32   812.5 1872.16   832.6 1874.65   852.7 1885.59
#Mann= 3 , 0 , 0
     9.9     .08       0     446    .045       0     461      .1       0
#XS Ineff= 2 , 0
          310.94 1802.26
Permanent Ineff=
       F       F
Bank Sta=446,461
XS Rating Curve= 0 ,0
Exp/Cntr=0.3,0.1

Type RM Length L Ch R = 1 ,191.2   ,47,48,49.1
XS GIS Cut Line= 4
      1808377.83       91202.003     1808172.671       91284.321
      1807939.65       91351.441     1807759.818       91460.353
#Sta/Elev= 30
      10  1881.7    40.2 1864.57    60.3 1859.11    70.3 1850.73    90.4 1847.88
   100.5 1839.54   110.5 1836.87   120.6  1830.5   140.7  1825.7   160.8 1815.63
   170.8 1814.25   190.9 1800.52     201 1797.49     211 1786.11   221.1 1780.15
   231.2  1779.3   241.3 1768.62   274.2 1766.86   281.7 1766.85   289.2 1766.97
   453.4 1768.13   463.6 1772.43   483.6 1774.58   503.6 1784.74   513.6 1786.86
   533.6 1798.89   543.6 1799.35   573.7 1807.74   593.7 1816.03   673.8  1817.4
#Mann= 3 , 0 , 0
      10     .08       0   274.2    .045       0   289.2     .08       0
Bank Sta=274.2,289.2
XS Rating Curve= 0 ,0
Exp/Cntr=0.3,0.1

Type RM Length L Ch R = 1 ,143.1   ,103,98.6,94.2
XS GIS Cut Line= 4
     1808401.892       91156.412     1808180.269       91243.795
     1807918.121       91307.116     1807763.618       91405.897
#Sta/Elev= 30
     9.9 1892.16    29.8 1889.16    39.7 1880.86    49.6 1880.15    69.5 1868.59
    79.4 1866.86    99.3 1855.58   109.2 1854.41     129 1843.24     139 1842.02
   158.8 1831.06   168.7 1830.63   178.7 1822.16   198.5 1817.41   228.3 1802.47
   238.2 1792.48   258.2 1784.66   268.2 1771.54   288.2 1769.14   298.2 1764.69
     438 1767.31   446.8 1764.51     458 1767.43   507.9 1768.55   527.2 1775.51
   565.8 1780.64   585.1 1792.88   633.4 1805.72   652.7 1814.45   691.3 1816.42
#Mann= 3 , 0 , 0
     9.9     .08       0     438    .045       0     458     .08       0
#XS Ineff= 2 , 0
          361.99 1774.83
Permanent Ineff=
       F       F
Bank Sta=438,458
XS Rating Curve= 0 ,0
Exp/Cntr=0.3,0.1

Type RM Length L Ch R = 1 ,44.5    ,51.3,44.5,37.8
XS GIS Cut Line= 4
     1808392.836       91116.039     1808250.026        91088.32
     1807885.719       91243.482     1807617.557       91511.643
#Sta/Elev= 30
     9.7 1880.05    29.1 1866.96    38.8 1865.57    58.2 1852.03    67.9 1850.38
    77.6 1842.09   116.4 1825.26   165.3 1807.03   185.1 1807.65   214.8 1801.28
   254.4  1782.9   274.2 1779.83   284.1 1772.59   343.5 1763.51   425.1 1763.39
   432.6 1763.32   440.1 1763.42   571.4 1766.57   631.3 1777.54   651.2 1789.93
   671.2 1792.03   701.1 1802.35   731.1 1804.87     751 1812.81     771 1808.72
   790.9 1814.99   820.9  1815.6   870.8 1825.36   890.7 1833.54   920.7 1833.28
#Mann= 3 , 0 , 0
       0     .08       0   425.1    .045       0   440.1     .08       0
Bank Sta=425.1,440.1
XS Rating Curve= 0 ,0
Exp/Cntr=0.3,0.1

Chan Stop Cuts=-1
Use User Specified Reach Order=0